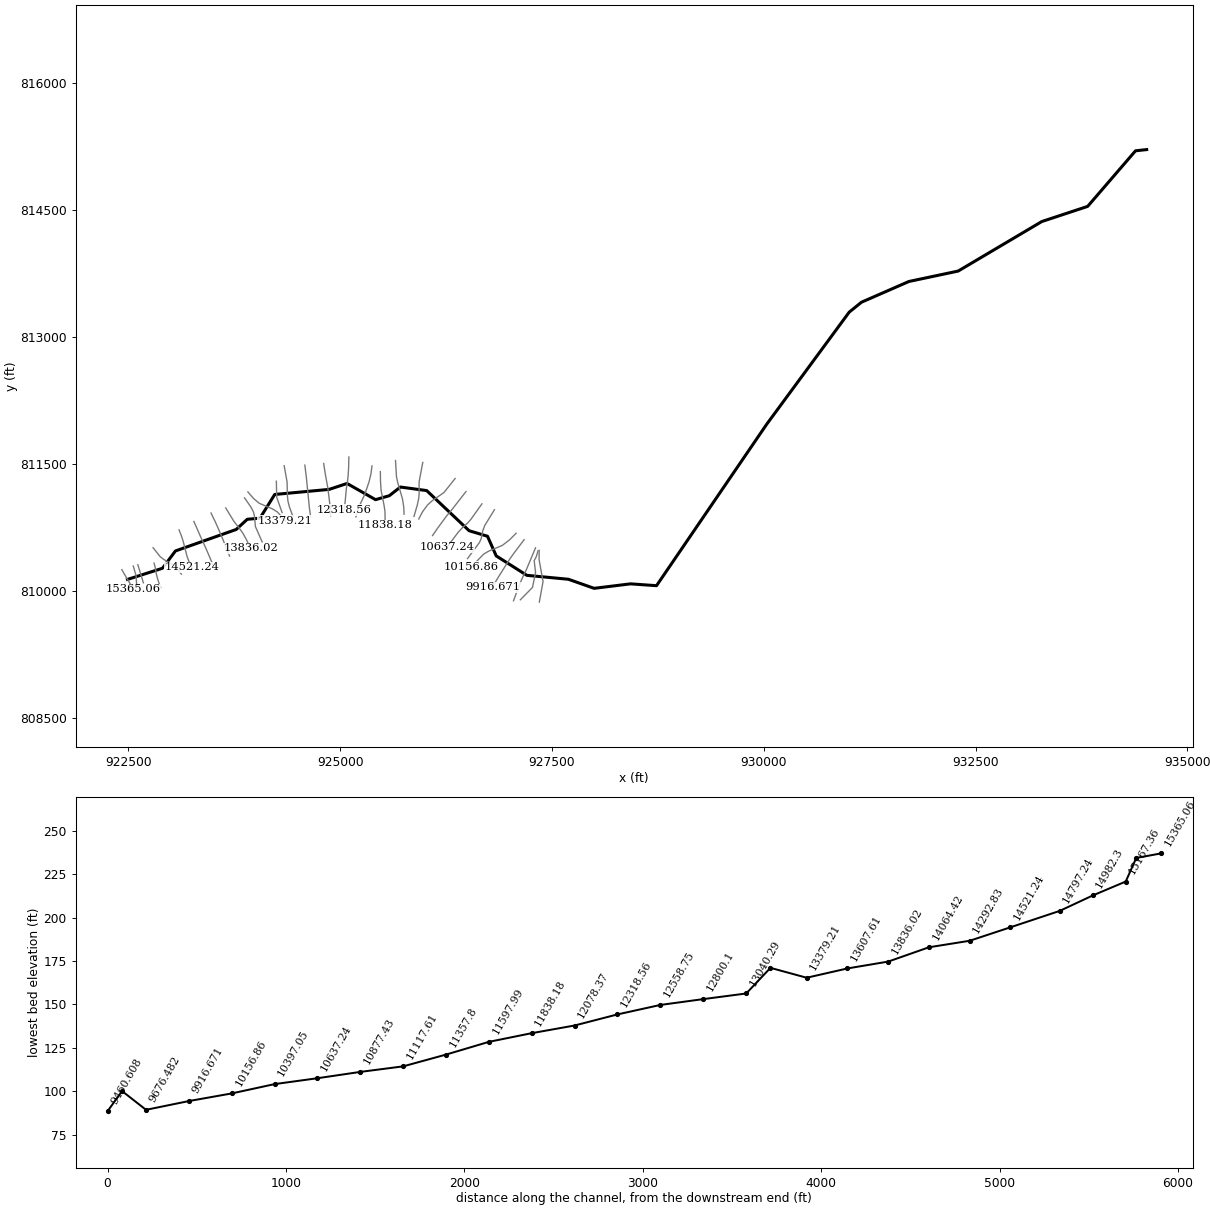
--- 15178_ras.prj (project) ---

Proj Title=15178
Current Plan=p01
Default Exp/Contr=0.3,0.1
English Units
Geom File=g01
Flow File=f01
Plan File=p01
Y Axis Title=Elevation
X Axis Title(PF)=Main Channel Distance
X Axis Title(XS)=Station
BEGIN DESCRIPTION:
RFD model 15178 exported to HEC-RAS
END DESCRIPTION:

--- 15178_ras.p01 (plan) ---

Plan Title=Plan 01
Program Version=4.10
Short Identifier=Plan 01
Geom File=g01
Flow File=f01
Subcritical Flow
Calc Critical at every XS
Secant Critical Depth

--- 15178_ras.f01 (steady flow) ---

Flow Title=Flow 01
Program Version=5.01
Number of Profiles= 6
Profile Names=10yr,25yr,50yr,100yr,100plus,500yr
River Rch & RM=15178,64,15365.06
  309.02  478.27  632.11  766.02  1118.4 1722.61
River Rch & RM=15178,64,15226.24
  315.23   488.3  645.74  782.94 1143.09 1757.17
River Rch & RM=15178,64, 14982.3
  596.98  922.02 1217.64 1473.01 2150.59 3006.06
River Rch & RM=15178,64,14797.24
   604.6   934.4 1234.52 1493.99 2181.23 3045.33
River Rch & RM=15178,64,14521.24
  608.41  940.58 1242.94 1504.46 2196.51 3064.88
River Rch & RM=15178,64,14292.83
  730.02  1134.7 1505.02 1827.34 2667.91 3646.23
River Rch & RM=15178,64,14064.42
  733.07 1139.65 1511.76 1835.71 2680.14 3661.42
River Rch & RM=15178,64,13836.02
  743.24 1156.36 1534.74 1864.47 2722.13  3714.4
River Rch & RM=15178,64,13607.61
  756.08 1177.28 1563.33 1900.08 2774.12 3779.08
River Rch & RM=15178,64,13379.21
  761.72 1186.75 1576.53 1916.79 2798.51 3810.51
River Rch & RM=15178,64, 13176.1
  812.04 1270.29 1692.08 2062.18 3010.78  4078.8
River Rch & RM=15178,64,13040.29
  814.37 1274.23 1697.58 2069.17 3020.99 4091.88
River Rch & RM=15178,64, 12800.1
  823.48 1289.59 1719.01 2096.35 3060.67 4142.62
River Rch & RM=15178,64,12558.75
  829.17 1299.19 1732.42 2113.37 3085.52 4174.38
River Rch & RM=15178,64,12318.56
  835.88 1310.52 1748.25 2133.44 3114.83  4211.8
River Rch & RM=15178,64,12078.37
  844.51 1325.14 1768.73  2159.5 3152.86 4260.53
River Rch & RM=15178,64,11838.18
  849.15 1333.23 1780.24 2174.34 3174.53  4289.1
River Rch & RM=15178,64,11597.99
  858.31 1349.26  1803.1 2203.84 3217.61    4346
River Rch & RM=15178,64, 11357.8
  863.22 1357.91 1815.49  2219.9 3241.05 4377.18
River Rch & RM=15178,64,11117.61
  867.45 1365.37 1826.18 2233.75 3261.27 4404.03
River Rch & RM=15178,64,10877.43
  868.34 1366.94 1828.43 2236.66 3265.52 4409.68
River Rch & RM=15178,64,10637.24
  878.57 1384.97 1854.23  2270.1 3314.34  4474.4
River Rch & RM=15178,64,10397.05
  884.64 1395.74 1869.72 2290.23 3343.74 4513.61
River Rch & RM=15178,64,10156.86
  887.21 1400.32 1876.32 2298.82 3356.28 4530.37
River Rch & RM=15178,64,9916.671
  894.51 1413.44 1895.31 2323.64 3392.51 4579.13
River Rch & RM=15178,64,9676.482
  898.59 1420.94 1906.31 2338.17 3413.73 4608.29
River Rch & RM=15178,64,9460.608
  902.41 1428.01 1916.71 2351.93 3433.82 4635.99
River Rch & RM=15178,64,9150.868
  904.51  1431.9 1922.42 2359.49 3444.86  4651.2
River Rch & RM=15178,64,9025.503
  905.09 1432.96 1923.98 2361.55 3447.87 4655.35
River Rch & RM=15178,64,8983.664
  905.66 1434.02 1925.54 2363.61 3450.87 4659.49
River Rch & RM=15178,64,8869.794
  906.23 1435.08 1927.09 2365.67 3453.88 4663.63
River Rch & RM=15178,64,8621.214
  907.19 1436.85 1929.69 2369.11 3458.89 4670.53
River Rch & RM=15178,64,8372.633
  912.83 1447.45 1945.41 2390.06 3489.48 4713.22
River Rch & RM=15178,64,8124.053
  913.82 1449.38 1948.33    2394 3495.24 4721.46
River Rch & RM=15178,64,7875.472
   917.4 1456.16 1958.39 2407.43 3514.85  4748.9
River Rch & RM=15178,64,7626.892
  940.95  1499.7 2022.44 2492.26  3638.7 4919.02
River Rch & RM=15178,64,7378.312
   946.1 1509.54 2037.14 2511.99 3667.51  4959.5
River Rch & RM=15178,64,7129.731
  954.65  1525.6 2060.99 2543.81 3713.96 5024.01
River Rch & RM=15178,64,6881.151
  957.14  1530.4  2068.2 2553.53 3728.15  5044.1
River Rch & RM=15178,64,6632.571
  959.32 1534.59 2074.48 2561.98 3740.49 5061.49
River Rch & RM=15178,64, 6383.99
  961.47 1538.74 2080.72 2570.39 3752.76 5078.85
River Rch & RM=15178,64, 6135.41
  965.26 1546.06 2091.73 2585.23 3774.44 5109.52
River Rch & RM=15178,64, 5886.83
  966.77 1549.07 2096.34 2591.52 3783.63 5122.83
River Rch & RM=15178,64,5638.249
  994.47 1601.24  2173.9 2695.21    3935 5332.66
River Rch & RM=15178,64,5389.669
 1000.98 1614.12 2193.55    2722 3974.11 5388.85
River Rch & RM=15178,64,5141.089
 1004.48 1621.04 2204.07 2736.33 3995.04 5418.82
River Rch & RM=15178,64,4892.508
 1063.58 1730.55 2365.74 2951.38 4309.02 5845.63
River Rch & RM=15178,64,4643.928
 1069.01 1741.19 2381.89 2973.36  4341.1 5891.03
River Rch & RM=15178,64,4395.348
 1072.79 1748.57  2393.1  2988.6 4363.36 5922.48
River Rch & RM=15178,64,4146.767
 1078.84 1760.38 2411.01 3012.95 4398.91 5972.66
River Rch & RM=15178,64,3898.187
 1082.27  1767.1 2421.23 3026.87 4419.24 6001.44
River Rch & RM=15178,64,3649.607
 1085.14 1772.81 2429.98 3038.85 4436.72 6026.42
River Rch & RM=15178,64,3401.026
 1445.19 2398.39 3322.18 4192.96 6121.72 8107.96
River Rch & RM=15178,64,3152.446
 1447.79 2403.48 3329.94 4203.56  6137.2 8129.06
River Rch & RM=15178,64,2888.446
  1466.6 2439.82 3384.97 4278.37 6246.41 8276.12
River Rch & RM=15178,64,2681.928
 1471.38 2449.16  3399.2 4297.81  6274.8 8314.65
River Rch & RM=15178,64,2475.411
 1476.31 2458.78 3413.84 4317.79 6303.98 8354.21
River Rch & RM=15178,64,2268.893
 1477.41 2460.92  3417.1 4322.24 6310.46 8362.99
River Rch & RM=15178,64,2062.375
 1482.14 2470.19 3431.24 4341.57  6338.7 8401.36
River Rch & RM=15178,64,1678.203
 1487.81  2481.3 3448.18 4364.74 6372.52 8447.31
River Rch & RM=15178,64,1149.009
 1491.06 2487.65 3457.86 4377.97 6391.84 8473.53
River Rch & RM=15178,64,       0
 1648.32 2791.07 3917.71 5004.05 7305.91 9692.23
Boundary for River Rch & Prof#=15178,64,1
Up Type= 0
Dn Type= 2
Boundary for River Rch & Prof#=15178,64,2
Up Type= 0
Dn Type= 2
Boundary for River Rch & Prof#=15178,64,2
Up Type= 0
Dn Type= 2
Boundary for River Rch & Prof#=15178,64,2
Up Type= 0
Dn Type= 2
Boundary for River Rch & Prof#=15178,64,2
Up Type= 0
Dn Type= 2
Boundary for River Rch & Prof#=15178,64,2
Up Type= 0
Dn Type= 2

--- 15178_ras.g01 (geometry) ---

Geom Title=15178
Program Version=4.10

River Reach=15178,64
Reach XY= 30
922488.384685099810134.601430416922901.809979916810266.648219764
923054.790935099810470.972958177923772.119681448810724.750103429
923902.509795666 810844.75126791924052.364336222810858.217032164
924226.778264225811137.780391291924869.044980258811197.655009121
925080.584180266811267.413930416925416.987115651811076.441708207
925579.747532308811123.099694282925710.161432773811225.472982153
926020.816498548811183.523377389926521.587810129810709.688235983
926738.601699024810644.584069297926841.683296233810412.379208192
927203.346018642810183.028555632927693.462810099810136.771569297
927997.085699707810029.612785861928426.659082115810082.475958392
928734.044407338810060.816708192930034.031023443 811965.83202669
931008.783990681813289.983374834931153.315240681813407.170874834
931713.211074024813651.962541506932295.229154766813775.136371538
933282.565943569814359.756915241933823.888157308814538.681291521
934388.992323995815194.931291476934520.502740681815209.254208148

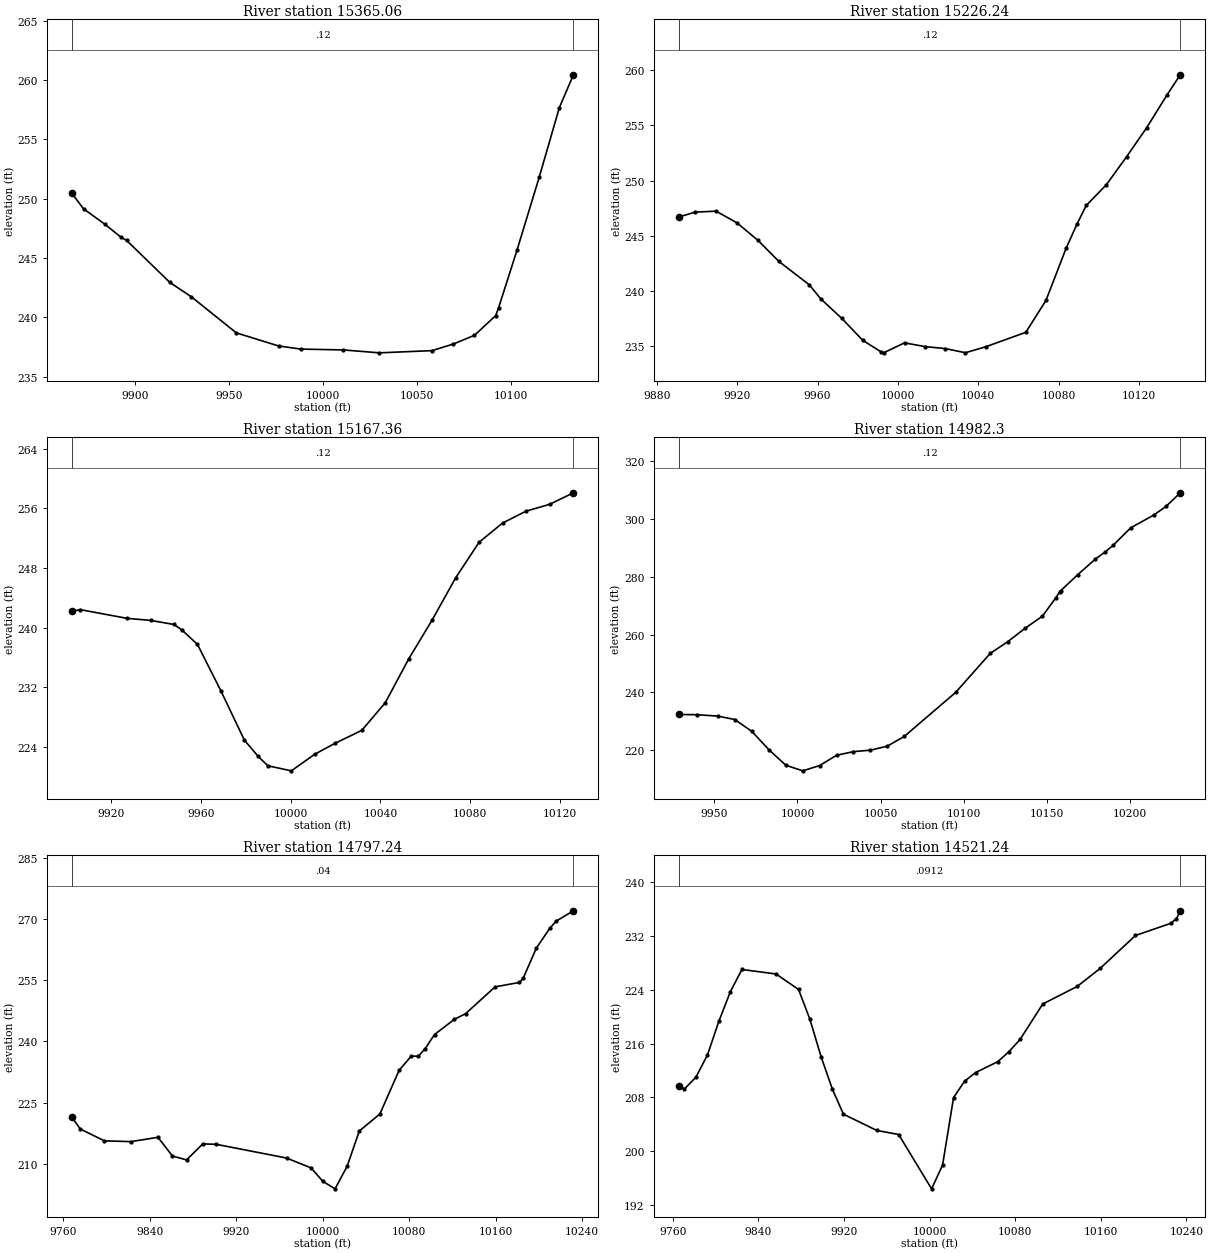
Type RM Length L Ch R = 1 ,15365.06,138.821900,138.821900,138.821900
XS GIS Cut Line= 6
922422.165199509810250.375896175922467.149412852810170.327271314
922488.662035168810135.988180882 922489.77143556810134.324080293
922510.905419493810099.755729133922553.397694407810018.365580255
#Sta/Elev= 21
9866.656250.44599872.823249.15159884.294247.83439892.855246.73989895.765246.4833
9918.706242.94769930.177241.73189954.091238.69259976.565237.58989988.366237.3284
10011.02237.2545 10030.2237.011210058.16 237.19710069.44 237.75210080.72238.4901
   10092240.150410093.58240.830310103.29 245.64510115.19251.839810125.85257.6799
10133.33260.4456
#Mann= 3 , 0 , 0
9866.656    0.12       09866.656    0.12       010133.33    0.12       0
#XS Ineff= 2 , 0
       09890.545                       0
Bank Sta=9866.656,10133.33
Exp/Cntr=0.3,0.1

Type RM Length L Ch R = 1 ,15226.24,58.878100,58.878100,58.878100
XS GIS Cut Line= 3
922556.786183428810292.781542411922589.872976464810179.501335747
922598.284872998810048.275749809
#Sta/Elev= 27
9891.015246.69279899.121247.13339909.539247.22269919.957 246.1599930.375244.5767
9940.793242.66569955.979240.54019961.628239.27139972.046237.51199982.464 235.524
9991.647234.46779992.882234.3827 10003.3 235.28810013.54234.948210023.56234.7693
10033.58 234.393 10043.6 234.92710063.64236.242510073.66239.130310083.68243.8552
10089.17246.0812 10093.7247.735810103.72249.620810113.74252.143310123.76  254.78
10133.78257.722110140.52259.5804
#Mann= 3 , 0 , 0
9891.015    0.12       09891.015    0.12       010140.52    0.12       0
#XS Ineff= 2 , 0
       0 9904.85                       0
Bank Sta=9891.015,10140.52
Exp/Cntr=0.3,0.1

Type RM Length L Ch R = 1 ,15167.36,185.064100,185.064100,185.064100
XS GIS Cut Line= 2
922610.622321249810308.483749275922676.235114218  810094.8215773
#Sta/Elev= 24
9902.504242.18389906.149242.4138 9927.07241.23919937.531240.96789947.992240.4187
9951.482239.69379958.453237.74699968.914231.50819979.375224.90649985.547 222.721
9989.836221.4741 10000.3220.795810010.76223.029410019.61224.462410031.68 226.222
10042.14229.9209 10052.6235.802610063.06241.020910073.52246.672610083.98251.4506
10094.44254.020610104.91255.613410115.37256.524610126.01258.0767
#Mann= 3 , 0 , 0
9902.504    0.12       09902.504    0.12       010126.01    0.12       0
#XS Ineff= 2 , 0
       09918.188                       0
Bank Sta=9902.504,10126.01
Exp/Cntr=0.3,0.1

Type RM Length L Ch R = 1 , 14982.3,185.064100,185.064100,185.064100
XS GIS Cut Line= 6
922802.035304992810327.417375546922812.730065326810288.898036048
922828.290638546810204.734318201922839.155326458810159.080304011
922855.832312695810104.500949757922880.512854914810036.952151876
#Sta/Elev= 30
9928.715232.29919939.797232.2198 9951.98231.73859962.358230.55879972.661 226.404
9982.845220.0882 9993.03214.709510003.19212.763110013.36214.596210023.52218.1608
10033.69 219.42310043.85219.927610054.01221.309710064.29224.714610095.13239.9535
10115.94253.481910126.39257.504710136.85262.167510147.31266.388210155.44272.8226
10157.76274.886510158.28275.2042 10168.4280.690210179.05286.1334   10185288.6317
10189.69 290.87910200.34296.999810214.14301.386910221.63304.4443 10230.2309.1474
#Mann= 3 , 0 , 0
9928.715    0.12       09928.715    0.12       0 10230.2    0.12       0
#XS Ineff= 2 , 0
       09942.684                       0
Bank Sta=9928.715,10230.2
Exp/Cntr=0.3,0.1

Type RM Length L Ch R = 1 ,14797.24,276.000000,276.000000,276.000000
XS GIS Cut Line= 6
922790.512740606810509.362043356   922874.635503810403.470948476
922914.483160632810371.803405658923029.809907804 810305.34610534
923077.538920737810258.896543484923124.380188849 810197.21849445
#Sta/Elev= 30
9768.041221.44279775.706218.55549798.091215.6395 9822.76215.44979847.597216.5088
9861.051211.91419874.121210.96899889.068214.89089901.414214.79699966.566211.4287
9989.202209.012110000.28205.686910011.47203.873510022.67209.438810033.87218.0468
10052.94222.237910070.68232.919410081.98236.434310088.33236.370910094.72 238.215
10103.47241.710410121.78 245.42410132.24 246.82610159.51253.395510182.01254.4759
10185.37255.451910197.73262.932310210.05267.7373 10215.9269.492310231.95272.0459
#Mann= 3 , 0 , 0
9768.041    0.04       09768.041    0.04       010231.95    0.04       0
#XS Ineff= 2 , 0
       09938.059                       0
Bank Sta=9768.041,10231.95
Exp/Cntr=0.3,0.1

Type RM Length L Ch R = 1 ,14521.24,228.405400,228.405400,228.405400
XS GIS Cut Line= 6
923097.051001199810719.821040414923122.682396157810654.906741114
 923144.65893695810589.091030954923192.556473028810403.612712333
923213.456731159810349.187778613923246.493546016810276.882509619
#Sta/Elev= 30
9765.693209.74589770.876209.25599781.627 211.0119792.379214.2845 9803.13219.3293
9813.881223.71549824.633226.99579856.471226.33329877.557 224.029  9888.1219.6271
9898.642214.04129909.111209.25619919.472205.52189950.551203.11179971.068202.5011
10001.86194.437210012.13197.9697 10022.4207.989410032.67210.411110042.94211.7019
10063.76213.316410074.19214.808410084.62216.626510105.73221.878810137.86224.4734
 10159.4227.162610192.39232.044310225.37233.8481 10230.7234.5561 10234.3235.7118
#Mann= 3 , 0 , 0
9765.693  0.0912       09765.693  0.0912       0 10234.3  0.0912       0
#XS Ineff= 2 , 0
       0                               0
Bank Sta=9765.693,10234.3
Exp/Cntr=0.3,0.1

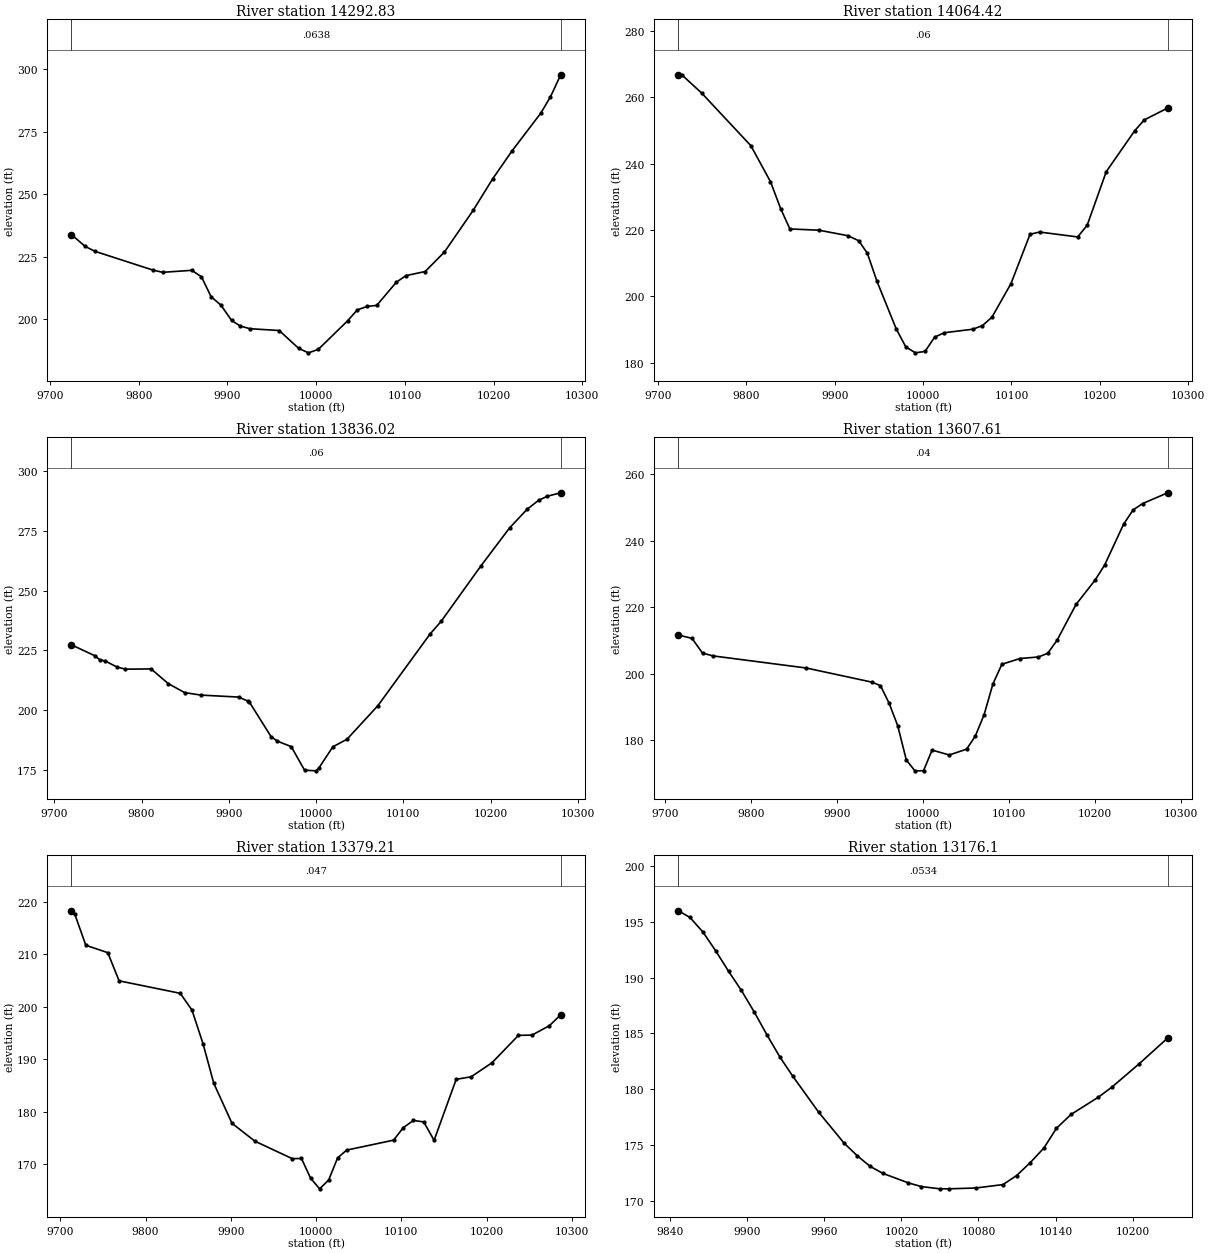
Type RM Length L Ch R = 1 ,14292.83,228.405300,228.405300,228.405300
XS GIS Cut Line= 6
923272.320023692810819.123378854923354.014481242810633.365852926
923384.011864659810568.139156002923384.913372104810566.353859296
923420.829866056810487.332846311923494.235833702810314.343703324
#Sta/Elev= 30
9724.278233.85869739.707229.15329750.631227.20529816.177 219.6879827.102218.8048
9859.875219.59989870.799 217.0299881.723209.03989892.648205.75659904.814199.5863
9914.497197.37499925.421196.29889958.428195.57889980.442188.42919991.448186.6673
10002.49188.056110035.44199.407710046.43203.809610057.41205.166110068.39205.6197
10090.33   214.8 10101.2217.480410122.92219.118510144.65226.904810177.24243.6427
10198.97256.085210220.69267.183210253.28282.350810264.14288.837710275.72297.6444
#Mann= 3 , 0 , 0
9724.278  0.0638       09724.278  0.0638       010275.72  0.0638       0
#XS Ineff= 2 , 0
       0                               0
Bank Sta=9724.278,10275.72
Exp/Cntr=0.3,0.1

Type RM Length L Ch R = 1 ,14064.42,228.405300,228.405300,228.405300
XS GIS Cut Line= 6
923474.709683631810918.722399484923521.196014646810822.914553542
923561.137240056810733.982036287923590.247208199810666.172419977
923601.075867099810640.699850486923693.561068154810410.482608213
#Sta/Elev= 30
9723.226266.75659727.363266.66329749.593261.22559805.168245.37389827.398234.5202
9839.001226.32619849.354220.27189882.241219.89599915.128218.22879927.206216.7137
9936.978 212.9549947.859204.47629969.619190.15569980.499 184.6999991.379182.9158
10002.27183.357310013.15187.662310024.01188.977510056.37190.038110067.15191.1218
10077.93193.658810099.48203.801210121.04218.666110131.81219.341510174.92217.8591
 10185.7221.395810207.25237.535710239.58249.928710250.36253.159910276.78256.7422
#Mann= 3 , 0 , 0
9723.226    0.06       09723.226    0.06       010276.78    0.06       0
#XS Ineff= 2 , 0
       0                               0
Bank Sta=9723.226,10276.78
Exp/Cntr=0.3,0.1

Type RM Length L Ch R = 1 ,13836.02,228.405400,228.405400,228.405400
XS GIS Cut Line= 6
923648.438954203810978.165836663923744.525849554810820.989446257
923826.549117724810715.128918945923854.490220804810673.671025952
923894.105438435810601.459992424923941.586709806810502.042196729
#Sta/Elev= 30
9719.613227.35179746.547 222.765 9752.08 221.0929758.173220.61699771.685218.0986
9781.425217.17099810.894217.28129830.498211.15449849.287207.37969867.771206.3381
9911.259205.5092 9921.71 203.844 9923.61203.3813 9948.31189.0225 9955.69187.0712
9971.487184.78849986.783174.94789999.697 174.66510003.14 175.82210019.24184.7352
10035.33187.846110070.84201.923910130.46231.801510143.33237.184710188.42260.1129
10221.67276.206110241.87284.039110254.92287.749310265.07289.497110280.36290.9263
#Mann= 3 , 0 , 0
9719.613    0.06       09719.613    0.06       010280.36    0.06       0
#XS Ineff= 2 , 0
       0                               0
Bank Sta=9719.613,10280.36
Exp/Cntr=0.3,0.1

Type RM Length L Ch R = 1 ,13607.61,228.405300,228.405300,228.405300
XS GIS Cut Line= 6
923870.084036347 811097.86491638923945.428319987 810989.46090325
923975.138757499810931.786460883923986.603802239810886.996978077
923998.773525702810758.785761022924078.193799142810578.686624897
#Sta/Elev= 30
9715.211211.61179731.008210.60869743.287206.16949755.566 205.324 9863.89201.6906
9940.167197.44669950.358196.39139960.512191.07899970.518184.30029980.523173.9957
9990.529170.722610000.53170.754110010.54 176.96910030.54175.496510050.68177.2457
 10060.8181.1686 10071.1187.632710081.39196.919410091.78202.806510112.87204.5441
10134.36205.004710145.15206.115310155.99210.034410178.14220.8282 10200.3228.1535
10211.37232.670810233.52244.9962 10244.6249.292710255.68 251.19310284.82254.4415
#Mann= 3 , 0 , 0
9715.211    0.04       09715.211    0.04       010284.82    0.04       0
#XS Ineff= 2 , 0
       0                               0
Bank Sta=9715.211,10284.82
Exp/Cntr=0.3,0.1

Type RM Length L Ch R = 1 ,13379.21,203.105100,203.105100,203.105100
XS GIS Cut Line= 6
923909.855135402811168.108068425923976.414067235811090.814247381
924043.649659722 811033.72646538924199.114153325810967.737482627
924257.034682063810932.132029865 924354.61184991810824.273169036
#Sta/Elev= 30
9713.103218.25879717.104  217.579729.976211.6999 9755.72210.28539769.009204.9325
9840.706202.55489854.459199.36669867.446192.9586 9880.02185.44489901.368 177.836
9928.259174.42489972.187 171.094 9982.84171.14569993.493167.405910004.11165.3622
 10014.7167.023710025.28171.259510035.86172.729710090.86174.621410102.23176.9955
10114.12178.376910126.26178.0864 10138.4174.596910164.33186.198110181.92186.6817
10206.26189.338410237.34194.558510253.29194.6112 10273.7196.412310286.91198.4589
#Mann= 3 , 0 , 0
9713.103   0.047       09713.103   0.047       010286.91   0.047       0
#XS Ineff= 2 , 0
       0                               0
Bank Sta=9713.103,10286.91
Exp/Cntr=0.3,0.1

Type RM Length L Ch R = 1 , 13176.1,135.810400,135.810400,135.810400
XS GIS Cut Line= 3
924245.957607707 811294.01685224924250.247805357811105.248155659
924313.528220688810923.987304964
#Sta/Elev= 30
9846.488196.01079855.507 195.409 9865.51194.11239875.513192.41729885.515190.5826
9895.518188.8588 9905.52186.92759915.523 184.8459925.525182.87639935.528181.1611
9955.533177.95289975.538175.14619985.541174.04529995.544173.087110005.55172.4495
10025.55171.590110035.57171.263610049.72171.066210056.75171.059710077.94171.1357
10099.12171.442610109.71172.2529 10120.3173.4105 10130.9174.716310140.74176.4957
10152.08 177.73710173.26179.278510183.85 180.18510205.04182.2745 10227.3184.5958
#Mann= 3 , 0 , 0
9846.488  0.0534       09846.488  0.0534       0 10227.3  0.0534       0
#XS Ineff= 2 , 0
       0                               0
Bank Sta=9846.488,10227.3
Exp/Cntr=0.3,0.1

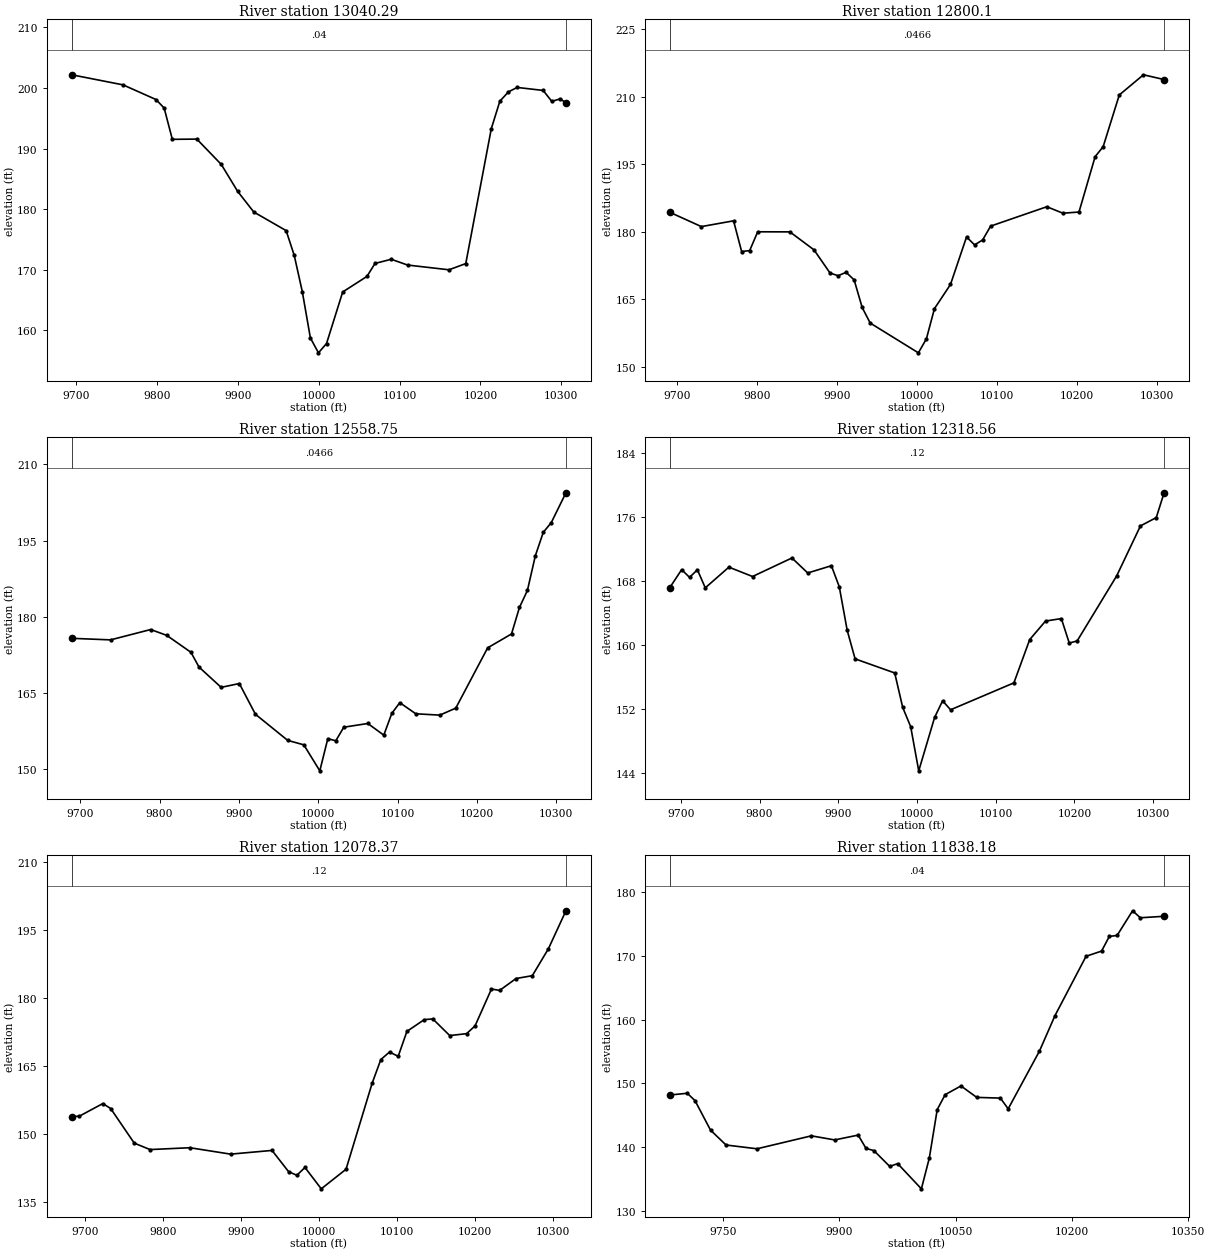
Type RM Length L Ch R = 1 ,13040.29,240.188800,240.188800,240.188800
XS GIS Cut Line= 6
924338.172451776811477.144721842924372.760949081811285.090008436
924376.458487049811119.642273885924383.024844386811058.355096535
 924400.26328309810989.950795555924441.692658867810878.703000361
#Sta/Elev= 30
9694.101202.16359757.623200.50179798.469198.07879808.576 196.6689818.683191.5125
9849.005191.55399879.326187.36329899.453182.94289919.494179.52279959.567176.4514
9969.567172.37699979.567166.39069989.567158.74869999.568156.286210009.57 157.825
10029.57166.326610059.58168.894910069.61171.039110089.68171.722910109.89170.7717
 10161.1169.988610181.93171.011510213.55193.278410224.12197.804810234.81199.3484
10245.53200.075810277.71199.580510288.44197.774410299.16198.207110305.92197.4876
#Mann= 3 , 0 , 0
9694.101    0.04       09694.101    0.04       010305.92    0.04       0
#XS Ineff= 2 , 0
       0                               0
Bank Sta=9694.101,10305.92
Exp/Cntr=0.3,0.1

Type RM Length L Ch R = 1 , 12800.1,241.357800,241.357800,241.357800
XS GIS Cut Line= 6
924582.379547553811484.148826468924599.951739312811341.425118904
924616.287851579811177.731584883924616.508322345811175.743773865
924634.811291473810990.430457465924650.857065562810869.399496656
#Sta/Elev= 30
9690.692184.28859730.136181.11339770.438182.39339780.514175.57439790.589175.7785
9800.665179.9593 9840.95179.93629871.099175.94249891.199170.79179901.248170.1933
9911.298170.95159921.348169.26939931.397163.13619941.447159.673310001.75153.0529
 10011.8 156.16310021.84162.867610041.94168.252810062.04178.811510072.09177.0461
10082.14178.139710092.19181.218210162.53185.529510182.62184.088610202.78184.3499
10222.96 196.64910233.04198.881810253.22210.371310283.48214.8566 10309.3213.7935
#Mann= 3 , 0 , 0
9690.692  0.0466       09690.692  0.0466       0 10309.3  0.0466       0
#XS Ineff= 2 , 0
       0                               0
Bank Sta=9690.692,10309.3
Exp/Cntr=0.3,0.1

Type RM Length L Ch R = 1 ,12558.75,240.188700,240.188700,240.188700
XS GIS Cut Line= 6
924804.619354996811503.386615526924822.667614177 811386.07031286
 924853.57521452811214.312887026924877.028555455811027.316196769
924881.837642238810971.489863474924886.600568155 810886.53085584
#Sta/Elev= 30
9689.287175.75849738.243175.45049788.831177.48899809.071176.33949839.553173.0076
9849.713170.10489877.617166.10769900.517166.86059920.838160.8084 9961.48155.6749
9981.802154.796910001.94  149.6810012.02156.0112 10022.1 155.59610032.18158.2657
10062.42158.998610082.58156.705310092.66160.987810102.74163.0944 10122.9 160.906
10153.14160.645510173.29162.022610213.44173.884310243.51176.619710253.53181.8383
10263.54 185.17610273.56192.020910283.57196.624110293.59198.520710312.09204.3992
#Mann= 3 , 0 , 0
9689.287  0.0466       09689.287  0.0466       010312.09  0.0466       0
#XS Ineff= 2 , 0
       0                               0
Bank Sta=9689.287,10312.09
Exp/Cntr=0.3,0.1

Type RM Length L Ch R = 1 ,12318.56,240.188800,240.188800,240.188800
XS GIS Cut Line= 6
 925101.85910281811579.986683097925099.346788386811459.943990888
925093.190630746811357.667727593925086.542310319811296.934720657
925073.099082268811212.878647441925048.585702016810955.094729062
#Sta/Elev= 30
9686.136167.12879701.126169.36869711.129168.40029721.131169.34779731.133167.0905
 9761.14 169.6789791.146168.50839841.213170.82439861.249168.94899891.303169.8555
9901.321167.2261 9911.35161.7948 9921.41158.21519971.725156.4538 9981.87152.1515
9992.014149.740810002.23144.222310022.45150.912910032.56152.972210042.67151.8524
10123.11155.2164 10143.2160.627110163.29162.939910183.38163.250210193.42  160.19
10203.47160.458210253.69 168.59310283.83174.831210303.92175.869110313.87178.9716
#Mann= 3 , 0 , 0
9686.136    0.12       09686.136    0.12       010313.87    0.12       0
#XS Ineff= 2 , 0
       0                               0
Bank Sta=9686.136,10313.87
Exp/Cntr=0.3,0.1

Type RM Length L Ch R = 1 ,12078.37,240.188700,240.188700,240.188700
XS GIS Cut Line= 6
925375.187589529811474.580244135925362.962615554811381.146213325
925341.006788503811289.090869198925289.457136271811138.136398598
925217.802956677810984.142529275 925185.21384058 810873.22417072
#Sta/Elev= 30
9682.956153.79529692.618153.85869722.874156.65499732.959155.56419763.215147.9233
9783.464146.50399834.601146.91069886.846145.49389939.968146.31489961.216141.6261
9971.785140.8306 9982.23142.553710003.12137.836810034.92142.161710068.38161.1346
10079.54166.366710090.69168.025310101.84167.0837   10113172.5838 10135.3175.1823
10146.25175.334710167.92 171.66410189.59 172.08410200.42173.798510221.48181.9352
10231.99181.626810253.01184.2508 10273.9184.881210294.54190.823410317.02199.2026
#Mann= 3 , 0 , 0
9682.956    0.12       09682.956    0.12       010317.02    0.12       0
#XS Ineff= 2 , 0
       0                               0
Bank Sta=9682.956,10317.02
Exp/Cntr=0.3,0.1

Type RM Length L Ch R = 1 ,11838.18,240.188800,240.188800,240.188800
XS GIS Cut Line= 6
 925473.69383127811407.471402706925475.625899787811288.858785598
925482.721186452811185.399655483925519.113137308811000.693522664
925528.444001591810932.274858704 925531.21243563810774.344233782
#Sta/Elev= 30
9681.106148.15329703.581148.42329713.582147.26819733.585142.63989753.587140.3017
9793.593139.70879863.691141.74129893.816141.09979924.107141.8586 9934.23  139.77
9944.396139.42249964.831 136.9379975.049 137.38210005.68133.420310015.89138.2433
 10026.1145.857910036.31 148.20410056.73149.574910077.14147.775410107.59147.6671
10117.68145.982410158.05155.0496 10178.1160.627610218.17 169.93210238.19170.7482
 10248.2  173.05 10258.2 173.201 10278.2177.0748 10288.2175.978810318.86176.2086
#Mann= 3 , 0 , 0
9681.106    0.04       09681.106    0.04       010318.86    0.04       0
#XS Ineff= 2 , 0
       0                10053.67       0
Bank Sta=9681.106,10318.86
Exp/Cntr=0.3,0.1

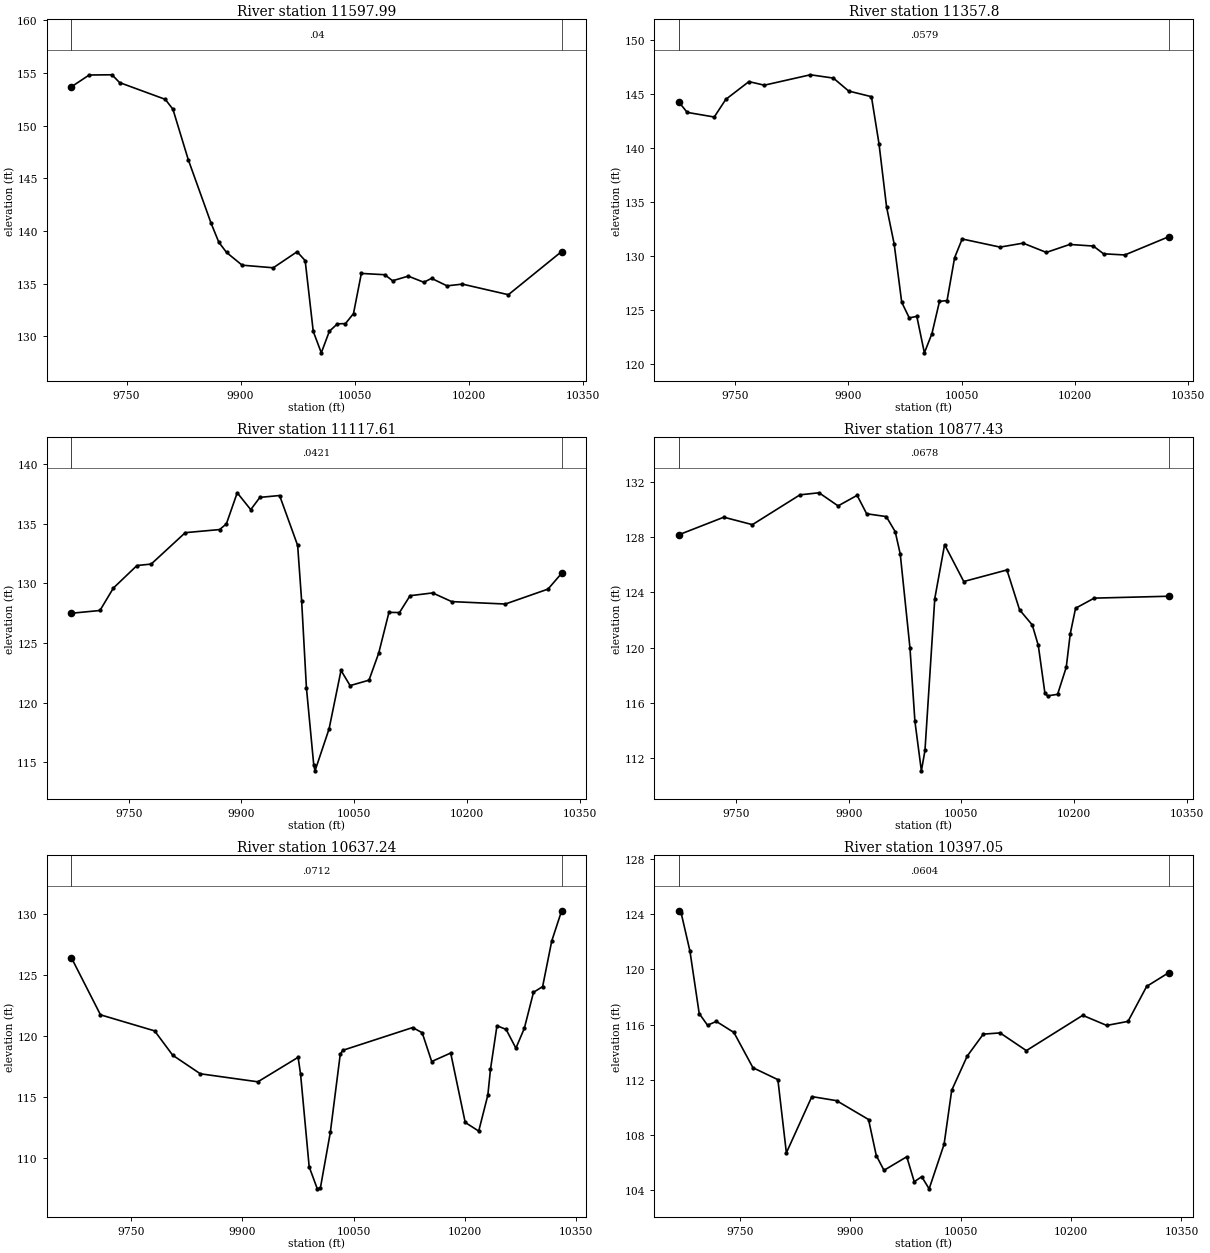
Type RM Length L Ch R = 1 ,11597.99,240.188700,240.188700,240.188700
XS GIS Cut Line= 6
 925652.68426952811538.286984097925663.905102317811348.543384505
925678.100774886 811280.26451027925734.753349109811086.338038272
925749.890491309810990.259730201925753.984091545810904.987610893
#Sta/Elev= 30
9677.525153.69439700.813154.80639730.814154.82829740.814154.0869 9800.94152.4949
9810.998151.55339831.113146.77789861.287140.7095  9871.4138.91889881.614137.9461
9902.041136.74069943.015136.49229974.371138.01629985.003137.17519995.634130.4528
10006.24 128.41310016.83130.462210027.42131.167810038.01131.1897 10048.6132.1441
10058.93135.957710089.76135.833510100.04135.2609 10120.6135.700410141.15 135.118
10151.32135.488710171.66134.777210191.93134.941310252.38133.935510322.48138.0389
#Mann= 3 , 0 , 0
9677.525    0.04       09677.525    0.04       010322.48    0.04       0
#XS Ineff= 2 , 0
       0                10095.53       0
Bank Sta=9677.525,10322.48
Exp/Cntr=0.3,0.1

Type RM Length L Ch R = 1 , 11357.8,240.188700,240.188700,240.188700
XS GIS Cut Line= 6
925974.602622001811515.922330312925931.380255572811287.407644223
925931.334219144811140.820912917925926.737327975811089.890173806
925909.206067856811010.746413176925870.791666979810878.939412395
#Sta/Elev= 30
9675.546144.27259686.704143.30469722.518142.87649737.783144.5053 9768.43146.1503
9788.862145.81869849.857146.78139880.236146.47499900.488145.27739930.626144.7564
9940.645140.40069950.664134.55839960.682131.1544 9970.69125.75459980.696124.3048
9990.701124.446710000.71121.074110010.71122.846510020.72 125.83210030.73125.9081
10040.73129.872610050.74131.600910100.93130.848910131.39131.214610162.17130.3582
10193.14131.094910224.39130.946910237.93130.229610266.05130.122910324.45131.8157
#Mann= 3 , 0 , 0
9675.546  0.0579       09675.546  0.0579       010324.45  0.0579       0
#XS Ineff= 2 , 0
       0                10132.05       0
Bank Sta=9675.546,10324.45
Exp/Cntr=0.3,0.1

Type RM Length L Ch R = 1 ,11117.61,240.188800,240.188800,240.188800
XS GIS Cut Line= 6
926356.625450122 811326.19643361926224.289253748811160.326373078
926086.471133319811064.356253042926032.327635944811015.175180962
925973.757103214810936.617909293925926.916555987810848.461803323
#Sta/Elev= 30
9673.845127.50319711.719127.73369729.619129.61629760.973131.50379779.926 131.626
9825.251134.25939870.938134.51949879.966134.99459894.395137.60329912.383136.1897
9924.562137.2168 9950.78137.37369974.796 133.1919980.119128.53929986.454121.2761
9996.219  114.799997.922114.289110016.66117.814610032.52122.707410044.61121.4352
10069.76121.891510082.69 124.16210096.29127.574510110.34127.5631 10124.4128.9733
10154.44129.206310179.77128.478510251.15128.275210307.93129.525910326.12130.8523
#Mann= 3 , 0 , 0
9673.845  0.0421       09673.845  0.0421       010326.12  0.0421       0
#XS Ineff= 2 , 0
       0                10208.05       0
Bank Sta=9673.845,10326.12
Exp/Cntr=0.3,0.1

Type RM Length L Ch R = 1 ,10877.43,240.188700,240.188700,240.188700
XS GIS Cut Line= 6
926485.112266694811172.324028796926303.533483033810939.712957889
926282.094559375810915.381740847 926256.00584527810884.409851178
926146.917035687810736.118483712926090.069662238810652.721238584
#Sta/Elev= 30
9673.476128.15419733.512129.4269 9771.57 128.887    9835131.04379860.372131.1915
9885.744130.24339911.116131.00559923.802129.67479949.933129.4709 9961.86128.3807
9968.568126.76279981.531119.96939988.113114.67169996.722111.0938 10001.5 112.564
10014.57123.544810027.65127.443610053.18124.7779 10110.7125.612510127.57 122.729
10144.45121.639210152.49120.158910161.32116.700310164.91116.5121 10178.2116.6249
10189.74118.582310195.07121.000910202.15122.845610226.94123.576910326.52123.7139
#Mann= 3 , 0 , 0
9673.476  0.0678       09673.476  0.0678       010326.52  0.0678       0
#XS Ineff= 2 , 0
       0                               0
Bank Sta=9673.476,10326.52
Exp/Cntr=0.3,0.1

Type RM Length L Ch R = 1 ,10637.24,240.188800,240.188800,240.188800
XS GIS Cut Line= 6
926673.017161201811027.116499331926542.728779579810844.303750142
926502.803140937810798.836745743 926440.59621153810743.314858509
 926394.40237378810693.782192054926258.995188439810514.155143778
#Sta/Elev= 30
9669.418126.42319708.523121.74869781.578 120.428 9805.93118.43059843.174116.9045
9920.805116.24489975.094118.25759978.431116.87179990.016109.2631   10001107.4521
10005.25107.5561 10018.6112.107110031.95 118.50710035.29118.830710129.64120.7027
10142.46120.277210155.27117.911510180.91118.6094 10200.5112.907310218.72112.1961
10231.03115.1561 10234.6117.275110243.35120.851510255.66120.549610268.88119.0063
10280.29120.6487 10292.6123.597410304.92124.064810317.23127.816510330.58130.2957
#Mann= 3 , 0 , 0
9669.418  0.0712       09669.418  0.0712       010330.58  0.0712       0
#XS Ineff= 2 , 0
       0                               0
Bank Sta=9669.418,10330.58
Exp/Cntr=0.3,0.1

Type RM Length L Ch R = 1 ,10397.05,240.188700,240.188700,240.188700
XS GIS Cut Line= 6
926820.217703518810957.713604962926706.039893841810770.684484034
926682.369226799810706.662414199926664.606236229810617.527833441
926643.970695139810571.014238907 926503.26445993810381.087320045
#Sta/Elev= 30
9666.952124.26339670.196124.10789682.149121.33449694.732116.79879706.054115.9493
9718.007116.22589741.913115.42179767.754112.86189801.651111.99529813.193106.6801
9847.816110.76439881.454110.46779924.856 109.0999935.355106.48279945.854105.4083
9976.802106.39379986.963 104.5799997.084104.944110007.21104.062610027.54107.3049
10037.86111.220610058.99113.7097 10080.8115.301910103.59115.390910139.32114.1036
 10215.9116.667510248.56115.933910277.51 116.229 10302.8118.769710333.05119.7742
#Mann= 3 , 0 , 0
9666.952  0.0604       09666.952  0.0604       010333.05  0.0604       0
#XS Ineff= 2 , 0
       0                               0
Bank Sta=9666.952,10333.05
Exp/Cntr=0.3,0.1

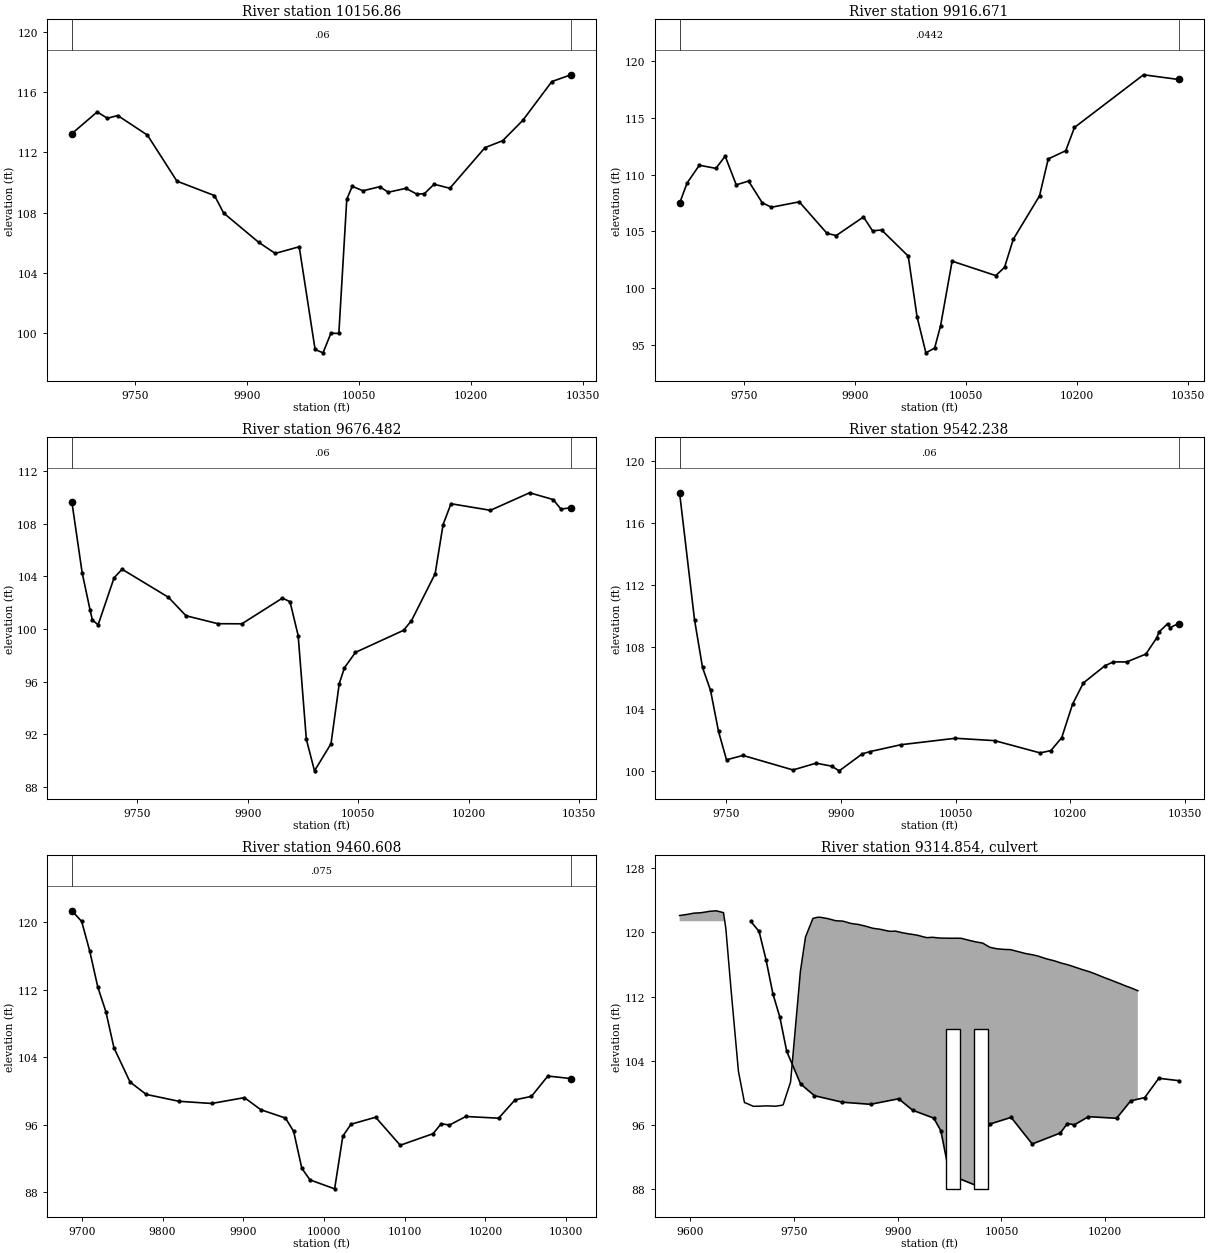
Type RM Length L Ch R = 1 ,10156.86,240.188800,240.188800,240.188800
XS GIS Cut Line= 6
927075.982929894810679.580952607927000.041182805 810602.93852483
 926913.20692906810536.325083472926750.711198089810467.717423132
926692.782607713810432.968411742926549.713994773810285.205734153
#Sta/Elev= 30
 9665.93113.2393 9699.73114.6772 9713.48114.25679727.259114.43929767.033113.1371
9806.494110.08619856.797109.12849869.007107.97169915.879106.03119938.058105.2904
9970.226105.73239991.47698.91757 10002.198.6943410012.6999.9982710023.2799.98269
10033.91108.887810041.23109.741610055.57109.447510078.05109.715810089.41109.3499
10113.11109.607910127.85109.219210137.88109.257510150.78109.881110171.89109.6127
10218.91112.308310242.57112.767110269.56114.119510308.43116.692210334.07117.1426
#Mann= 3 , 0 , 0
 9665.93    0.06       0 9665.93    0.06       010334.07    0.06       0
#XS Ineff= 2 , 0
       0                               0
Bank Sta=9665.93,10334.07
Exp/Cntr=0.3,0.1

Type RM Length L Ch R = 1 ,9916.671,240.188700,240.188700,240.188700
XS GIS Cut Line= 6
927171.039057626810604.189408044927045.370322776810437.239197953
927003.052988064810377.459860749926973.747343482810332.177281598
926862.463652575810154.960221261926796.446419773810044.254913784
#Sta/Elev= 30
9662.858107.4755  9672.9109.25179689.528110.8319 9711.91110.55439724.426111.6327
9739.412109.1047 9756.04109.43319774.492107.52469787.008107.12779824.557107.6045
9862.106104.82129874.564104.6361 9911.32106.27119923.572105.05129935.824 105.122
9971.815102.82239983.72697.475589995.63894.2956710007.4794.7182410015.46  96.672
10031.09102.374710090.13101.103210101.94101.838510113.75104.309710149.17108.1289
10160.98111.3877 10184.6112.110910196.41114.162510289.72118.804310337.16118.3894
#Mann= 3 , 0 , 0
9662.858  0.0442       09662.858  0.0442       010337.16  0.0442       0
#XS Ineff= 2 , 0
       09912.789                       0
Bank Sta=9662.858,10337.16
Exp/Cntr=0.3,0.1

Type RM Length L Ch R = 1 ,9676.482,134.243700,134.243700,134.243700
XS GIS Cut Line= 6
 927305.74579686810507.786637965927195.785389527810245.959392258
927157.609929757810168.698786339927132.918549625810112.421242311
927089.643072332810002.351258879 927045.60548804 809882.25729533
#Sta/Elev= 30
9661.102109.61049674.971104.26789685.817101.42349688.854100.68929696.663100.3183
9718.355103.88449729.201104.53569792.157102.4087 9815.97101.00839859.354100.4041
9891.892100.39579946.888102.34179957.253102.07719968.359 99.50889979.46591.63714
 9990.5789.2424410012.9891.30038 10024.295.8675710031.2797.0675410046.2398.23063
10111.4499.8997110122.19100.624410154.42 104.19410165.17107.912710175.91109.5041
10229.48109.005810282.73110.335310314.69109.821910325.34109.096110338.91109.2034
#Mann= 3 , 0 , 0
9661.102    0.06       09661.102    0.06       010338.91    0.06       0
#XS Ineff= 2 , 0
       09908.681        10103.36       0
Bank Sta=9661.102,10338.91
Exp/Cntr=0.3,0.1

Type RM Length L Ch R = 1 ,9542.238,81.630000,81.630000,81.630000
XS GIS Cut Line= 6
927335.846488297810473.681027517927314.464695305810402.956635311
927289.793395698810356.903542727927306.248840928810216.552712396
927269.790507585 810040.33743462927126.962818265809894.727863461
#Sta/Elev= 30
9689.442 117.9379708.958109.76299719.405106.69259729.852 105.2199740.299102.5738
9750.746 100.7479772.354101.02759837.622100.09429867.821100.52899887.953  100.34
 9898.02100.03619928.219101.13119938.328101.27549978.609101.716710049.81 102.133
10101.14101.980810160.49101.191210174.63 101.33910188.78 102.17310202.92104.3225
10217.06 105.69310245.35106.805310256.33107.048210273.63107.048310298.75107.5521
 10312.9108.596110316.06108.986210327.04109.4981 10330.2109.253410341.56109.5206
#Mann= 3 , 0 , 0
9689.442    0.06       09689.442    0.06       010341.56    0.06       0
#XS Ineff= 2 , 0
       09933.155         10104.7       0
Bank Sta=9689.442,10341.56
Exp/Cntr=0.3,0.1

Type RM Length L Ch R = 1 ,9460.608,309.739900,309.739900,309.739900
XS GIS Cut Line= 4
927348.927567977 810477.04928747927347.409514091810370.785515435
927394.469184564810109.680247005927350.445621863 809866.79162521
#Sta/Elev= 30
 9687.65 121.3889699.701120.12649709.702116.61699719.703112.34489729.704109.4317
9739.705105.15459759.707101.08789779.70999.622419820.12698.80852 9860.7798.54713
9901.41599.239429921.73797.80434 9952.2296.821999962.38195.251879972.54390.85838
9982.704 89.486810013.1988.4287710023.3594.6746110033.51 96.088110063.9996.91644
10094.48 93.594810135.1394.96649 10145.396.1479310155.4695.9879910175.7997.00546
10216.4496.8021710236.7698.9750210257.0999.3894810277.42 101.79910306.08101.5004
#Mann= 3 , 0 , 0
 9687.65   0.075       0 9687.65   0.075       010306.08   0.075       0
#XS Ineff= 2 , 0
       0 9937.05        10068.38       0
Bank Sta=9687.65,10306.08
Exp/Cntr=0.3,0.1

Type RM Length L Ch R = 2 ,9314.854,,,
Bridge Culvert--1,0,-1,-1, 0
Deck Dist Width WeirC Skew NumUp NumDn MinLoCord MaxHiCord MaxSubmerge Is_Ogee
33.37,243,2.6,0,87,87, , , 0.95, 0, 0,0,,
 9584.84 9594.45 9597.84 9605.22 9615.99 9624.77 9626.76 9637.53 9648.30 9651.70
 9659.07 9669.85 9678.62 9680.62 9691.39 9702.16 9705.55 9712.93 9723.70 9732.47
 9734.47 9745.24 9756.01 9759.40 9766.78 9777.55 9784.25 9786.27 9788.34 9799.16
 9809.98 9812.46 9820.80 9831.62 9838.66 9842.43 9853.25 9864.07 9864.85 9874.89
 9885.71 9891.05 9896.53 9907.35 9917.24 9918.17 9928.99 9939.81 9943.44 9944.50
 9950.35 9960.68 9971.01 9981.34 9982.87 9991.6610001.9910012.3210022.6510022.86
10032.9810043.3010053.6310062.8610063.9610074.2910084.6210094.9410102.8510105.27
10115.6010125.9310136.2610142.8410146.5810156.9110167.2410177.5710182.8410187.90
10198.2210208.5510218.8810222.8310229.2110239.5410247.13
  122.11  122.23  122.28  122.40  122.46  122.58  122.62  122.70  122.47  120.47
  113.00  102.69   98.76   98.71   98.30   98.32   98.34   98.35   98.31   98.43
   98.48  101.34  111.79  115.12  119.42  121.75  121.89  121.89  121.89  121.72
  121.47  121.45  121.41  121.14  121.04  121.01  120.79  120.52  120.51  120.39
  120.18  120.13  120.17  119.95  119.80  119.80  119.64  119.39  119.34  119.36
  119.39  119.30  119.28  119.27  119.28  119.27  119.04  118.83  118.67  118.67
  118.15  117.96  117.88  117.85  117.83  117.60  117.37  117.21  117.05  116.98
  116.69  116.47  116.18  116.03  115.95  115.65  115.35  115.08  114.91  114.74
  114.38  114.04  113.69  113.56  113.33  113.00  112.72
                                                                                
                                                                                
                                                                                
                                                                                
                                                                                
                                                                                
                                                                                
                                                                                
                                                        
 9584.84 9594.45 9597.84 9605.22 9615.99 9624.77 9626.76 9637.53 9648.30 9651.70
 9659.07 9669.85 9678.62 9680.62 9691.39 9702.16 9705.55 9712.93 9723.70 9732.47
 9734.47 9745.24 9756.01 9759.40 9766.78 9777.55 9784.25 9786.27 9788.34 9799.16
 9809.98 9812.46 9820.80 9831.62 9838.66 9842.43 9853.25 9864.07 9864.85 9874.89
 9885.71 9891.05 9896.53 9907.35 9917.24 9918.17 9928.99 9939.81 9943.44 9944.50
 9950.35 9960.68 9971.01 9981.34 9982.87 9991.6610001.9910012.3210022.6510022.86
10032.9810043.3010053.6310062.8610063.9610074.2910084.6210094.9410102.8510105.27
10115.6010125.9310136.2610142.8410146.5810156.9110167.2410177.5710182.8410187.90
10198.2210208.5510218.8810222.8310229.2110239.5410247.13
  122.11  122.23  122.28  122.40  122.46  122.58  122.62  122.70  122.47  120.47
  113.00  102.69   98.76   98.71   98.30   98.32   98.34   98.35   98.31   98.43
   98.48  101.34  111.79  115.12  119.42  121.75  121.89  121.89  121.89  121.72
  121.47  121.45  121.41  121.14  121.04  121.01  120.79  120.52  120.51  120.39
  120.18  120.13  120.17  119.95  119.80  119.80  119.64  119.39  119.34  119.36
  119.39  119.30  119.28  119.27  119.28  119.27  119.04  118.83  118.67  118.67
  118.15  117.96  117.88  117.85  117.83  117.60  117.37  117.21  117.05  116.98
  116.69  116.47  116.18  116.03  115.95  115.65  115.35  115.08  114.91  114.74
  114.38  114.04  113.69  113.56  113.33  113.00  112.72
                                                                                
                                                                                
                                                                                
                                                                                
                                                                                
                                                                                
                                                                                
                                                                                
                                                        
BR Coef=-1 , 0 , 0 ,, 0 ,,,0.8,-1,,0,
WSPro=,,,, 1 ,,,, 0 ,,,, 0 ,,,,-1 ,-1 ,-1 , 0 , 0 , 0 , 0 , 0
Multiple Barrel Culv=2,20,20,243,0.013,0.7,1,8,3,88,84,2,Culvert #1, 0, 33.37
 9980.00 9980.0010020.0010020.00
Culvert Bottom n=0.013
BC Design=,, 0 ,, 0 ,,,,,,