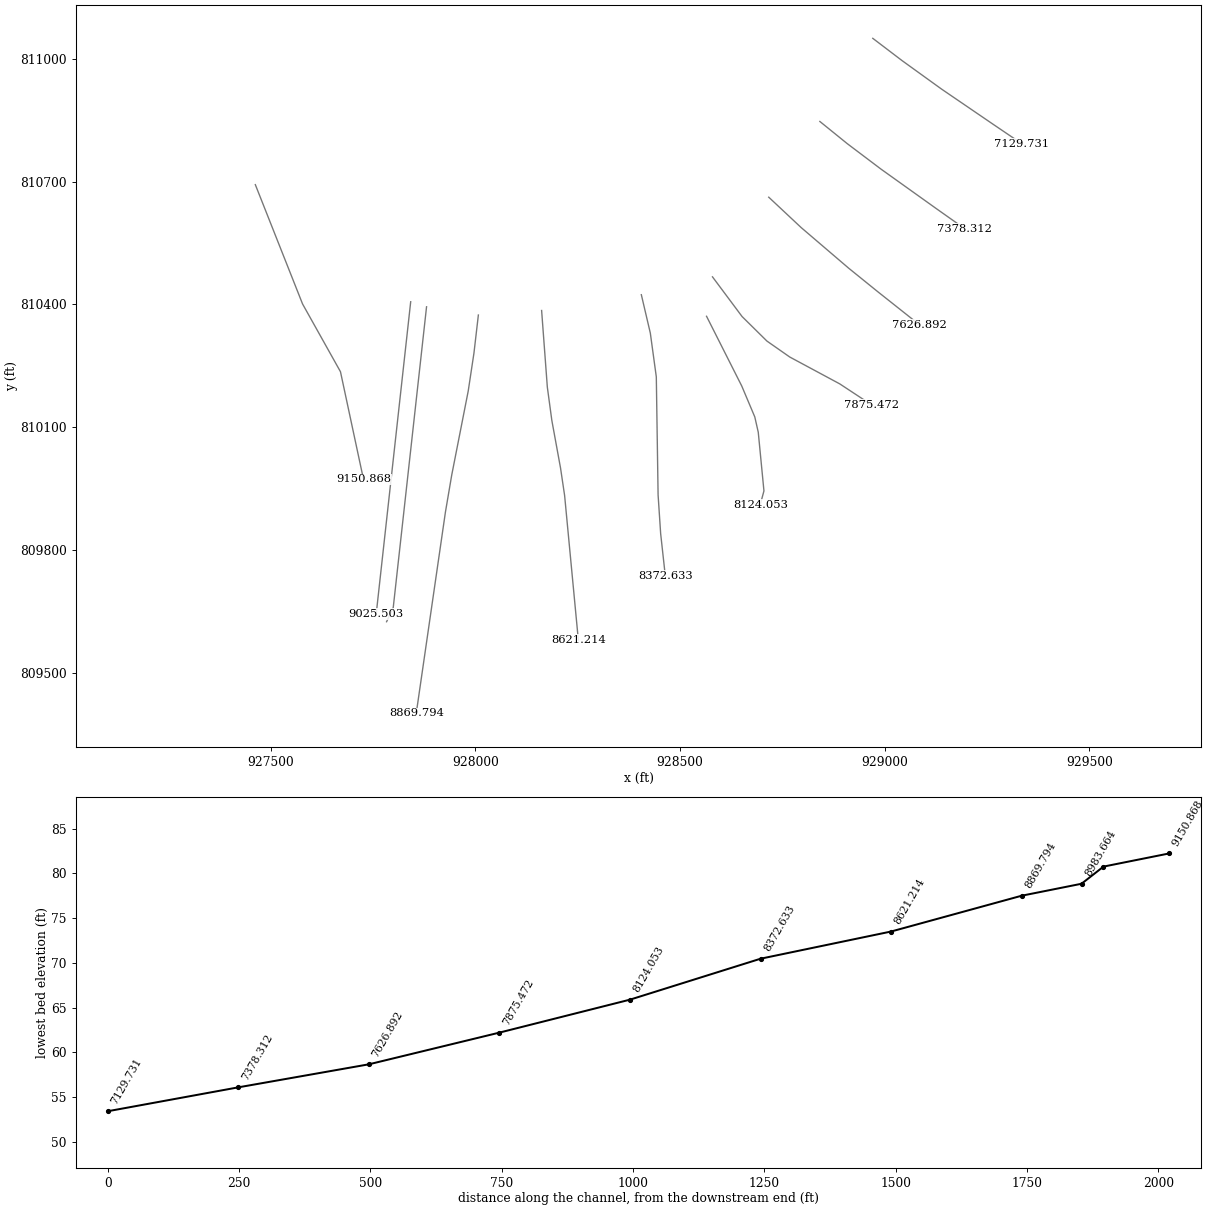
HEC-RAS study 15178_ras.prj: 15178

--- 15178_ras.g01 (geometry) --- (continued)

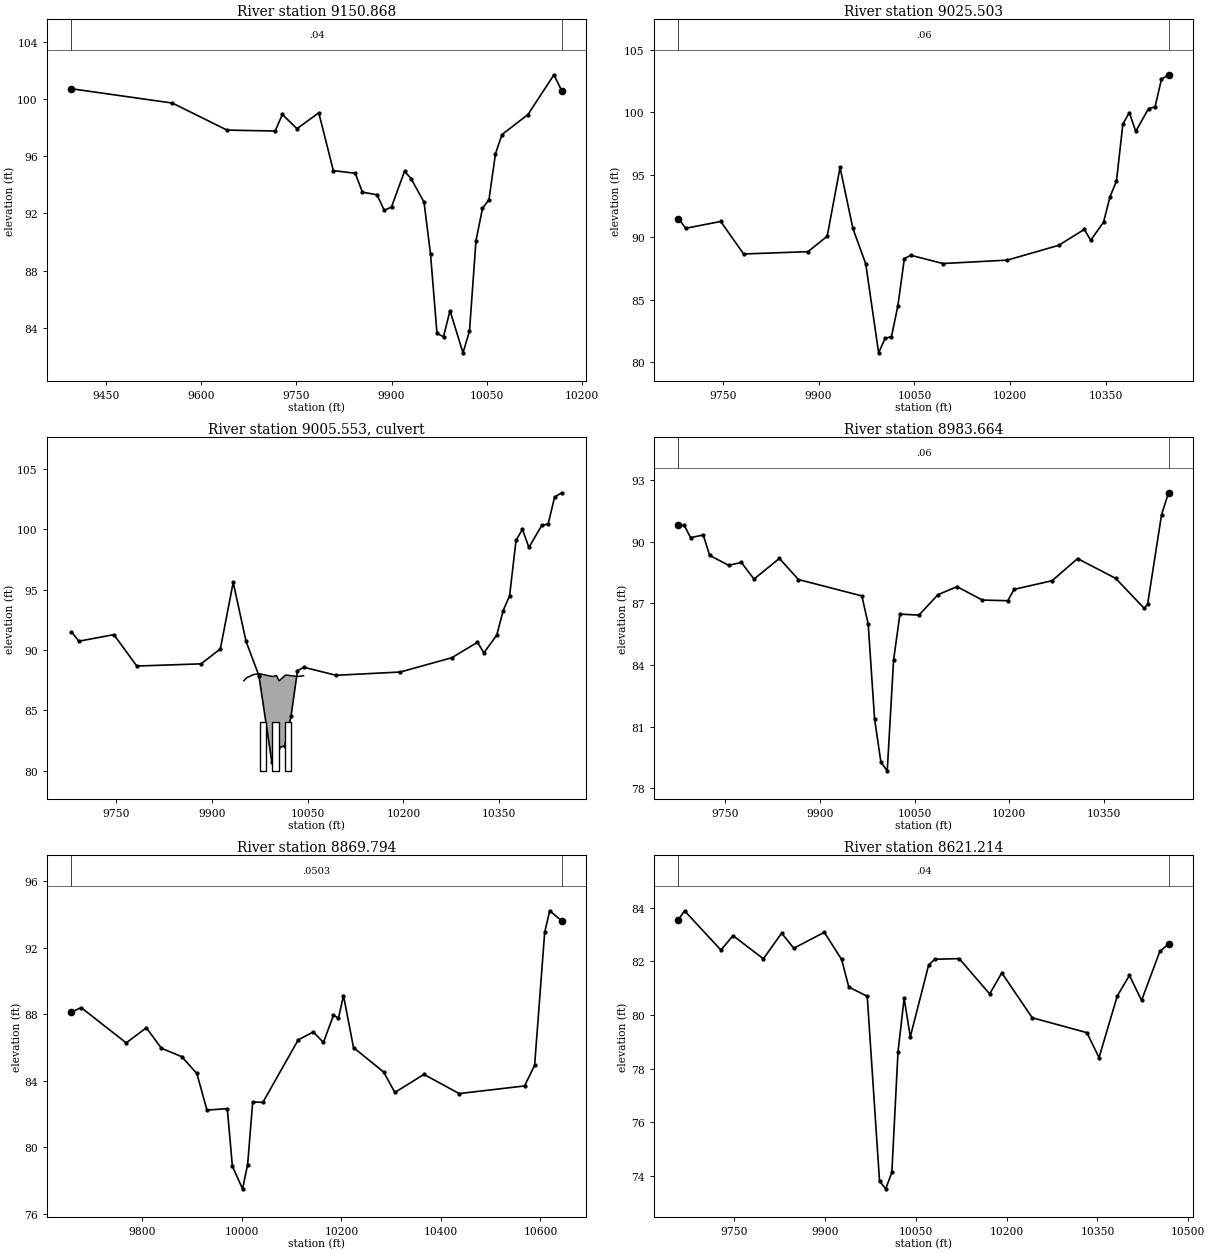
Type RM Length L Ch R = 1 ,9150.868,125.365800,125.365800,125.365800
XS GIS Cut Line= 4
927462.781609443810692.612939313927578.153704796810401.146593159
927670.754991855810235.678719561927726.922985645809973.055397245
#Sta/Elev= 30
9396.083100.7334 9554.8499.732749640.87997.837899716.597 97.77289728.056  98.933
9750.97597.938269785.354  99.0489808.27294.998989842.65194.81504 9854.1193.48866
9877.02993.306859888.48992.208739899.86492.454349920.31794.957449930.543 94.4428
9950.99592.796779961.22189.161469971.44783.588949981.674 83.3642  9991.985.18577
10012.3582.2331510022.5883.76127 10032.890.0897910043.03 92.349810053.2692.96988
10063.48 96.178910073.71 97.524110114.6198.9265510155.52101.713910167.73100.6022
#Mann= 3 , 0 , 0
9396.083    0.04       09396.083    0.04       010167.73    0.04       0
#XS Ineff= 2 , 0
       09926.425        10084.57       0
Bank Sta=9396.083,10167.73
Exp/Cntr=0.3,0.1

Type RM Length L Ch R = 1 ,9025.503,41.838500,41.838500,41.838500
XS GIS Cut Line= 2
927842.284647638810406.582373741927758.017850447809643.954548902
#Sta/Elev= 30
9680.48591.500949692.13890.726799746.81391.269779782.68588.670419883.29488.85222
9913.47690.088079933.59895.59392 9953.7290.708149973.84287.874449993.96380.76006
10004.0281.9083810014.0982.0660410024.15 84.527110034.2188.2908110044.2788.56728
10094.5787.9054110195.1888.1769910275.6789.3589710315.9190.6349610325.9789.76601
10346.0991.2261810356.1593.2588210366.2294.4902410376.2899.0727310386.3499.98093
 10396.498.4819210416.52100.304610426.58100.426910436.64102.651310447.75103.0062
#Mann= 3 , 0 , 0
9680.485    0.06       09680.485    0.06       010447.75    0.06       0
#XS Ineff= 2 , 0
       09839.946        10135.31       0
Bank Sta=9680.485,10447.75
Exp/Cntr=0.3,0.1

Type RM Length L Ch R = 2 ,9005.553,,,
Bridge Culvert--1,0,-1,-1, 0
Deck Dist Width WeirC Skew NumUp NumDn MinLoCord MaxHiCord MaxSubmerge Is_Ogee
10.919,20,2.6,0,12,12, , , 0.95, 0, 0,0,,
 9950.18 9954.79 9964.93 9975.06 9985.19 9995.3310001.1310005.4610015.6010025.73
10035.8710043.65
   87.45   87.70   87.96   88.04   87.91   87.80   87.89   87.45   87.93   87.86
   87.81   87.87
                                                                                
                
 9950.18 9954.79 9964.93 9975.06 9985.19 9995.3310001.1310005.4610015.6010025.73
10035.8710043.65
   87.45   87.70   87.96   88.04   87.91   87.80   87.89   87.45   87.93   87.86
   87.81   87.87
                                                                                
                
BR Coef=-1 , 0 , 0 ,, 0 ,,,0.8,-1,,0,
WSPro=,,,, 1 ,,,, 0 ,,,, 0 ,,,,-1 ,-1 ,-1 , 0 , 0 , 0 , 0 , 0
Multiple Barrel Culv=2,4,9.84,20,0.013,0.7,1,8,3,80,78,3,Culvert #1, 0, 10.919
 9980.32 9980.3210000.0010000.0010019.6810019.68
Culvert Bottom n=0.013
BC Design=,, 0 ,, 0 ,,,,,,

Type RM Length L Ch R = 1 ,8983.664,113.870200,113.870200,113.870200
XS GIS Cut Line= 3
927881.023742259 810394.30662404927799.643533945809659.714610174
927783.367492259809624.992387936
#Sta/Elev= 30
9675.45390.782979684.81790.792649694.878  90.191    971590.320559725.06189.32931
9755.24588.845059775.36788.98311 9795.4988.176489835.73489.179299865.918 88.1533
 9966.5387.355859976.59185.977669986.65281.376839996.71379.2684410006.77 78.8439
10016.8484.24324 10026.986.4694610057.0886.4222610087.26 87.418210117.4587.80544
10157.6987.1536410197.9487.12159   1020887.6757810268.3688.0967810308.6189.17332
10368.9888.2110110414.5486.7464410419.7586.9648210441.8391.3139510452.8992.37475
#Mann= 3 , 0 , 0
9675.453    0.06       09675.453    0.06       010452.89    0.06       0
#XS Ineff= 2 , 0
       09838.879        10135.93       0
Bank Sta=9675.453,10452.89
Exp/Cntr=0.3,0.1

Type RM Length L Ch R = 1 ,8869.794,248.580300,248.580300,248.580300
XS GIS Cut Line= 6
928007.569760869810374.170507119 927996.80574648810281.388562189
927982.787312675810188.487748744927942.509849615809983.388957888
927927.125430381 809892.90466947927855.809734128809401.170260707
#Sta/Elev= 30
9657.74988.138239677.04888.414169767.72786.28996 9808.1887.197369838.51985.96261
 9879.15 85.46339909.64884.448249929.99382.245259970.83482.334739981.04578.87146
10001.4777.5091710011.6878.9662710021.8882.7390710042.2982.7081810113.3686.47202
10143.7986.9472410163.98 86.314110184.1587.9486210194.2487.7786210204.3389.13314
 10224.586.0067910285.1184.5336510307.4883.3078910365.9884.3947910436.7583.24029
10568.1783.6989610588.3984.9420810608.61 92.940610618.71 94.2366 10642.893.63001
#Mann= 3 , 0 , 0
9657.749  0.0503       09657.749  0.0503       0 10642.8  0.0503       0
#XS Ineff= 2 , 0
       09852.047        10146.73       0
Bank Sta=9657.749,10642.8
Exp/Cntr=0.3,0.1

Type RM Length L Ch R = 1 ,8621.214,248.580400,248.580400,248.580400
XS GIS Cut Line= 6
928162.063866434810385.218897147928176.023480531810197.979682314
928187.031708024810116.625516016928208.297529884810000.239551022
928218.229352233809933.307675859 928251.72444767809580.613620082
#Sta/Elev= 30
9657.33783.558949667.57683.894029727.69882.427539747.73882.965499797.89382.10133
9828.02183.06022 9848.1282.494419898.57683.090499927.20982.076059939.02481.04778
9969.51480.70073 9989.8473.7987610000.0173.5104710010.1874.1207210020.3578.61808
10030.5180.6265310040.6879.1867810071.0481.8704410081.1582.0842910121.5482.10778
10171.8380.7888510191.9481.5739910242.1779.8995210332.5479.3433410352.6278.40954
10382.7580.7141810402.8381.4808210422.9180.5473810453.0382.3748110467.4882.65106
#Mann= 3 , 0 , 0
9657.337    0.04       09657.337    0.04       010467.48    0.04       0
#XS Ineff= 2 , 0
       09906.942        10110.08       0
Bank Sta=9657.337,10467.48
Exp/Cntr=0.3,0.1

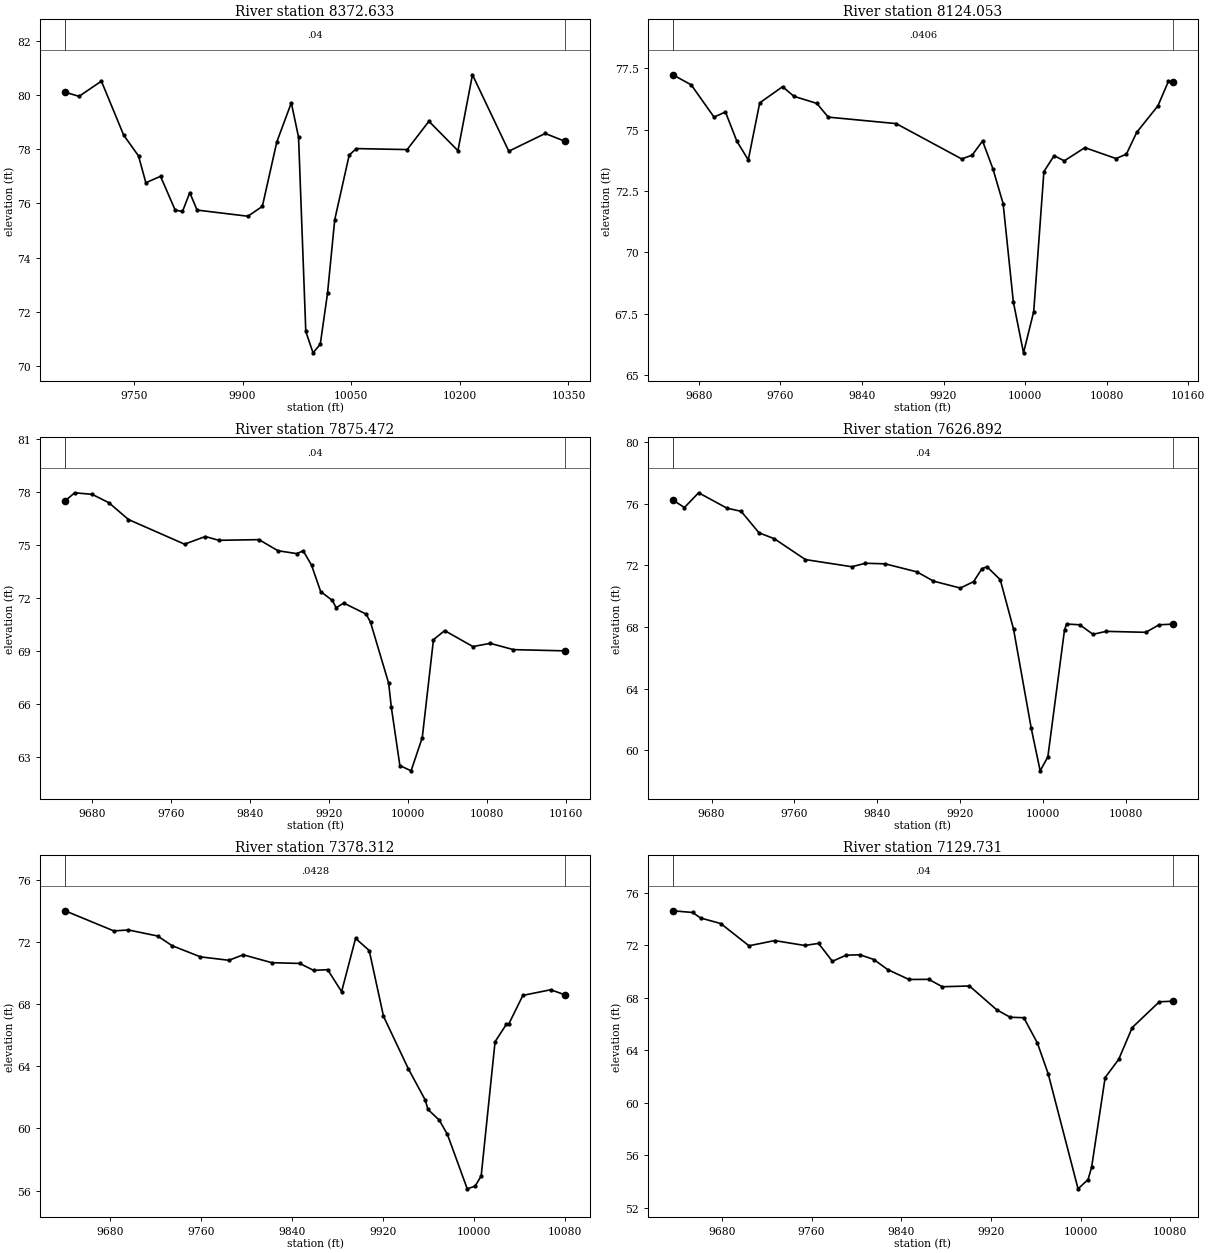
Type RM Length L Ch R = 1 ,8372.633,248.580300,248.580300,248.580300
XS GIS Cut Line= 6
928405.615762487810423.799484193928427.583891766 810329.99756828
928442.197279285810223.100004105928446.554657948809934.855102546
928452.824974839809840.026224869928464.066529545809737.926049421
#Sta/Elev= 30
9654.83280.11873 9674.1479.966289704.95280.528499735.76378.529599756.23477.76083
9766.36476.768599786.62477.005819806.88475.756029816.98275.704499827.03676.40253
9837.08975.757039907.25275.528689927.27175.892769947.27778.281839967.27779.72592
9977.27778.452069987.27771.263059997.27770.4725110007.2870.7928710017.2872.67784
10027.2875.4073710047.2877.7965210057.2878.0326610127.2977.9956710157.32 79.0438
10197.41 77.954610217.4580.7643110267.6677.9355710317.96 78.5916 10345.278.30267
#Mann= 3 , 0 , 0
9654.832    0.04       09654.832    0.04       0 10345.2    0.04       0
#XS Ineff= 2 , 0
       09961.054        10117.81       0
Bank Sta=9654.832,10345.2
Exp/Cntr=0.3,0.1

Type RM Length L Ch R = 1 ,8124.053,248.580400,248.580400,248.580400
XS GIS Cut Line= 6
 928564.88626992810371.097731141928650.881529235810200.786252312
928682.768259724810125.191151938928691.211818006 810087.89275964
928705.100042146809944.557607304 928696.06038517809911.017265915
#Sta/Elev= 30
9654.42977.243719672.46276.834849694.86775.51813 9706.0775.727219717.27274.53301
9728.47473.769399739.67776.096949762.08276.757249773.284 76.36499795.68976.07657
9806.89275.516219873.54375.252079937.75973.811859948.01273.964019958.26574.54222
9968.44573.409229978.44871.98752 9988.4567.985349998.45265.9018210008.4667.58381
10018.4673.2971910028.4773.9425310038.4773.7331910058.6574.2721310089.1373.82728
10099.3474.0047410109.55 74.899510130.2675.9743910140.6276.9782110144.7476.96552
#Mann= 3 , 0 , 0
9654.429  0.0406       09654.429  0.0406       010144.74  0.0406       0
#XS Ineff= 2 , 0
       09896.134         10052.6       0
Bank Sta=9654.429,10144.74
Exp/Cntr=0.3,0.1

Type RM Length L Ch R = 1 ,7875.472,248.580300,248.580300,248.580300
XS GIS Cut Line= 6
928579.394930865810467.395570877928651.677070581810370.461662798
 928712.40256662810310.535684292928768.183749393810271.559919709
 928890.24107307 810205.98951986928968.057447251810154.790312043
#Sta/Elev= 30
9652.74877.509459662.45577.971779680.179 77.88269697.092  77.4089716.92476.45683
9773.72575.060279794.77675.494919808.39175.279259849.09575.317679868.29874.68972
9887.44374.524499893.90274.683319902.34373.871479911.54772.379429923.43271.87298
9927.21671.461049934.96271.723689957.69171.096419962.06970.634349980.42167.18757
9983.11665.831379991.78662.5206910003.14 62.221110014.4864.1031610025.8169.65196
10037.1570.1641910065.7769.2604210083.2269.4430710106.8669.0870310158.9769.01718
#Mann= 3 , 0 , 0
9652.748    0.04       09652.748    0.04       010158.97    0.04       0
#XS Ineff= 2 , 0
       09927.318        10039.37       0
Bank Sta=9652.748,10158.97
Exp/Cntr=0.3,0.1

Type RM Length L Ch R = 1 ,7626.892,248.580300,248.580300,248.580300
XS GIS Cut Line= 6
928716.803224706810661.965704664928796.117086701810587.677708164
928911.875392828 810488.72074393928986.173962971810428.639776883
928987.766962888810427.430499717929085.327710637810350.091434195
#Sta/Elev= 30
9642.48776.238819653.71875.750199667.41976.705659694.82275.707999708.52375.50479
9725.81974.108079740.44773.732479770.66972.374589815.46871.911149828.62472.13639
9847.61772.099369878.39671.578799894.40470.978659920.32870.528259933.18870.94649
9941.17471.781769946.04971.910459958.90971.070669971.76967.860849988.88561.42483
 9997.4958.6797710004.9159.5876510021.0167.8172910022.99 68.196210035.7568.14823
10048.5167.5299710061.27 67.721710099.5667.6593610112.3268.14714 10125.568.18964
#Mann= 3 , 0 , 0
9642.487    0.04       09642.487    0.04       0 10125.5    0.04       0
#XS Ineff= 2 , 0
       09914.178        10052.07       0
Bank Sta=9642.487,10125.5
Exp/Cntr=0.3,0.1

Type RM Length L Ch R = 1 ,7378.312,248.580400,248.580400,248.580400
XS GIS Cut Line= 6
928841.684935375810846.908235922928908.734220089810792.632899309
928991.229362881810730.379649151929129.004869743810632.011781152
929130.636621227810630.855326616929195.242457077810585.254132245
#Sta/Elev= 30
  9640.174.010589682.96272.714319695.82872.775529721.559 72.38539734.21371.76604
9759.26971.043649784.32570.823129796.85371.177739822.04270.667879846.63370.62031
 9858.9270.172669871.20770.219499883.494 68.80299895.78172.235369907.80971.44845
9920.356  67.2219942.22863.838019957.21761.810699959.43861.225029969.50560.52831
9976.64859.608049994.07956.10799   1000156.2820410006.3456.9350910018.5865.58347
 10028.566.6983310030.8266.7468410043.0668.5631610067.5468.9254510080.0868.59928
#Mann= 3 , 0 , 0
  9640.1  0.0428       0  9640.1  0.0428       010080.08  0.0428       0
#XS Ineff= 2 , 0
       09919.248        10074.37       0
Bank Sta=9640.1,10080.08
Exp/Cntr=0.3,0.1

Type RM Length L Ch R = 1 ,7129.731,248.580300,248.580300,248.580300
XS GIS Cut Line= 6
928970.937297314811049.981978043929042.632820989 810995.44586518
929138.943747066810925.996079121929266.063445298810839.253415337
929267.727902853 810838.14455058929334.849350392810792.702857995
#Sta/Elev= 30
9636.28574.615249653.95474.485169661.03274.066119679.08373.642149704.211 71.9494
9727.12872.344979753.94171.97302 9766.2772.130649778.59970.768419790.92871.23457
9803.25671.264789815.58570.904019827.91470.137999846.87269.383839864.54369.39265
9876.64968.830549900.86268.887789925.07567.080389937.18166.505239949.28766.47201
9961.394 64.55249971.06362.202579997.71353.4388910006.6154.1456110009.7855.07856
10021.8661.9165510033.9363.2969410046.0165.7214310070.1667.6841810082.0667.72758
#Mann= 3 , 0 , 0
9636.285    0.04       09636.285    0.04       010082.06    0.04       0
#XS Ineff= 2 , 0
       09922.862        10081.62       0
Bank Sta=9636.285,10082.06
Exp/Cntr=0.3,0.1