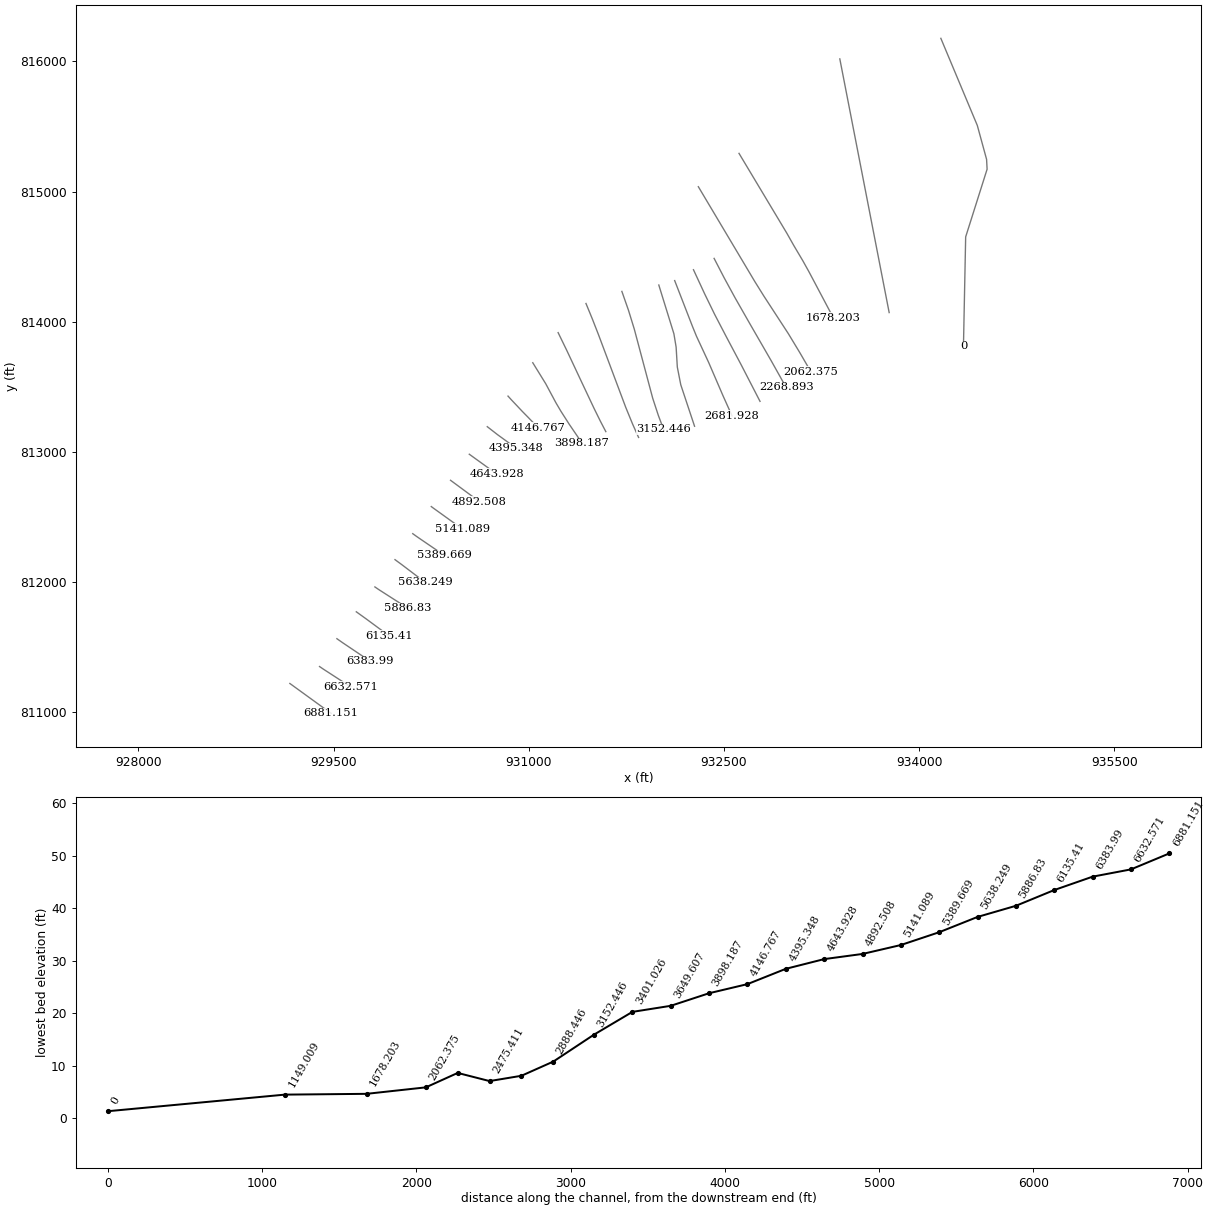
HEC-RAS study 15178_ras.prj: 15178

--- 15178_ras.g01 (geometry) --- (continued)

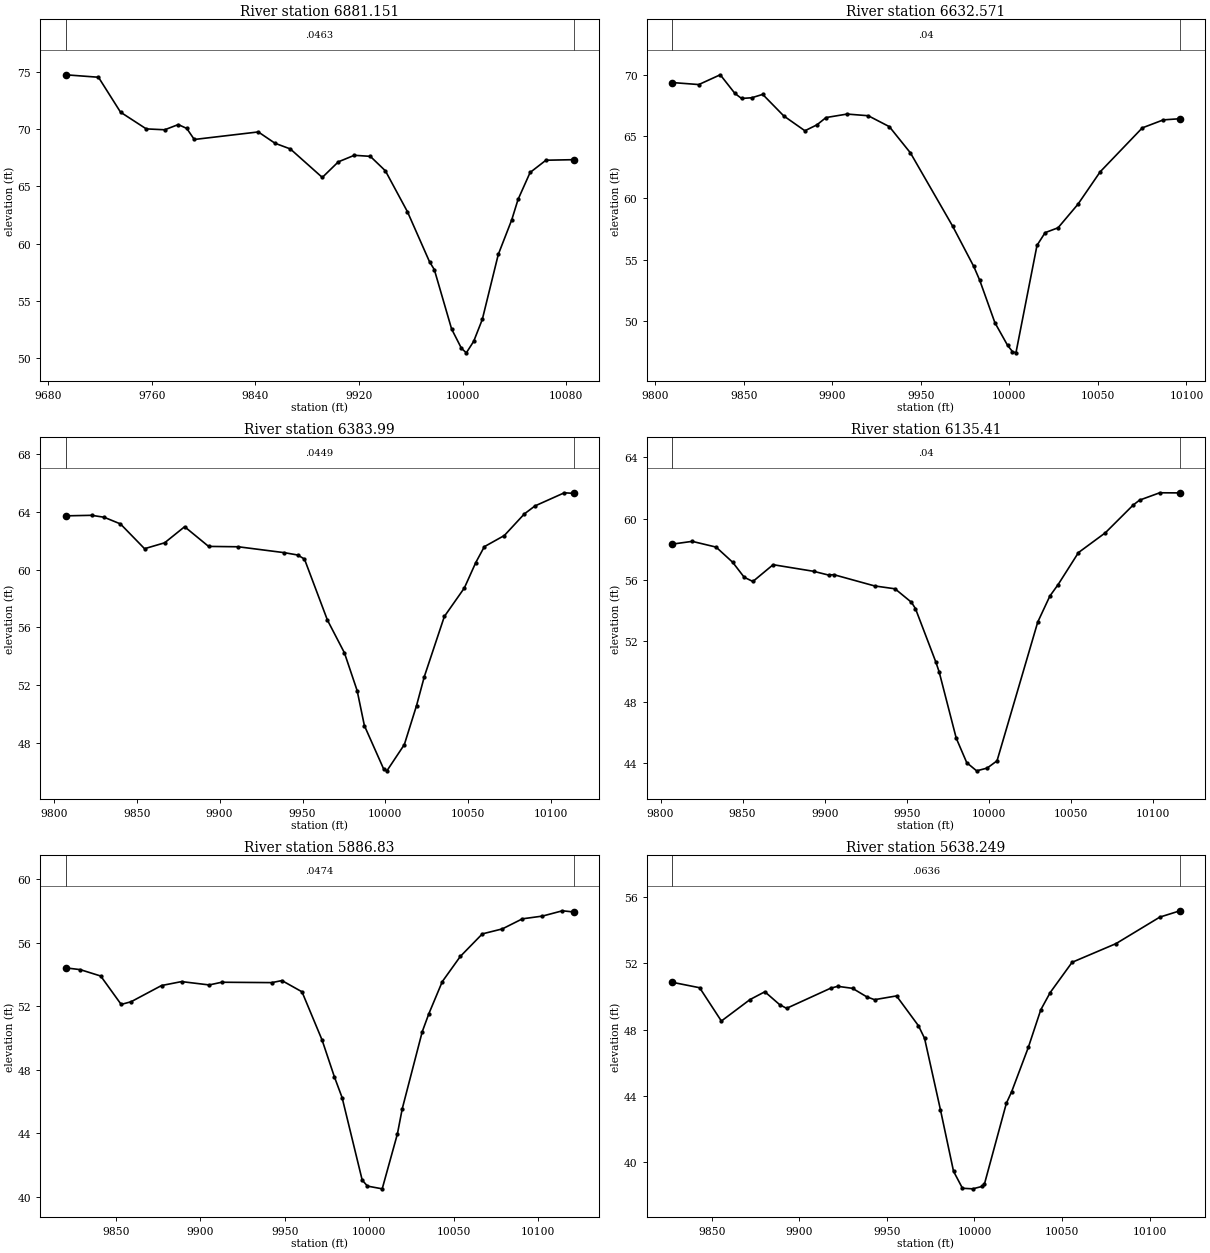
Type RM Length L Ch R = 1 ,6881.151,248.580400,248.580400,248.580400
XS GIS Cut Line= 5
 929164.52733912811219.932253585929411.943416653811040.551303394
 929413.55680795811039.369369163929443.428239073811017.804626879
929482.397550535 810990.30764324
#Sta/Elev= 30
9693.39974.717069718.83874.501829735.87471.458599755.74170.001879769.94769.92507
9780.44470.378139786.98470.043359792.79669.079189842.20369.736589855.12968.74853
9866.90668.25638 9891.6165.771189903.96267.129169916.31367.700969928.66567.60949
9940.31266.347269957.34862.778719974.38558.420759978.07257.741279991.42152.56408
    999950.8831510002.7850.4873710008.4651.4886210015.1153.3987710027.45 59.0624
10037.8462.0782910042.7163.85527   1005266.2024210064.2467.2718410085.5467.31894
#Mann= 3 , 0 , 0
9693.399  0.0463       09693.399  0.0463       010085.54  0.0463       0
#XS Ineff= 2 , 0
       0 9912.16                       0
Bank Sta=9693.399,10085.54
Exp/Cntr=0.3,0.1

Type RM Length L Ch R = 1 ,6632.571,248.580300,248.580300,248.580300
XS GIS Cut Line= 5
929392.483617186811350.206429383929421.871817434811330.168997118
929551.009931166811246.461039836929552.701650344811245.394228596
929632.910883697811193.818628923
#Sta/Elev= 30
9809.53669.368659824.68569.203279836.788 69.99679845.10568.479229848.83368.07633
9854.60868.13361 9860.75 68.40719872.66766.657669884.58465.455739891.37865.93699
9896.50166.527079908.41866.810619920.33566.674969932.252   65.79 9944.1763.65938
9968.00457.715929979.92154.449149983.30153.323739991.83849.89222    999948.05359
10001.7347.5511910003.7347.4441110015.6256.1613810020.2257.1939410027.5157.58663
10038.7159.4920810051.2962.1272310075.0765.6901910086.9566.3391210096.3666.43235
#Mann= 3 , 0 , 0
9809.536    0.04       09809.536    0.04       010096.36    0.04       0
#XS Ineff= 2 , 0
       09903.298                       0
Bank Sta=9809.536,10096.36
Exp/Cntr=0.3,0.1

Type RM Length L Ch R = 1 , 6383.99,248.580300,248.580300,248.580300
XS GIS Cut Line= 5
929525.983207381811564.052441193929568.579141487811534.117203817
 929684.68282588811456.053919158929686.351708112811454.951724939
 929779.60030015811391.995478395
#Sta/Elev= 30
 9807.0363.717739822.77463.754439830.27463.622089840.16663.158849854.71861.44301
 9866.8361.850599878.88162.964119893.35561.601189911.27861.575949939.13161.16626
9947.122 61.00469951.18260.724219965.04456.495829975.28254.233769982.96751.61152
9987.332 49.1916    999946.1748610000.91 46.059110011.4347.8760210018.7950.57595
 10023.552.5880810035.5756.7482810047.6358.7212110054.53  60.484 10059.761.58276
10071.7662.3554810083.8363.8515910090.2764.4060210107.96 65.315110113.5165.27467
#Mann= 3 , 0 , 0
 9807.03  0.0449       0 9807.03  0.0449       010113.51  0.0449       0
#XS Ineff= 2 , 0
       09893.103        10112.02       0
Bank Sta=9807.03,10113.51
Exp/Cntr=0.3,0.1

Type RM Length L Ch R = 1 , 6135.41,248.580400,248.580400,248.580400
XS GIS Cut Line= 6
929674.988550233 811770.70897726929753.272929372811714.359002147
929830.162286485 811657.61924231929831.762380839811656.419368126
929908.805634364 811599.89009988929925.132225395811588.463577477
#Sta/Elev= 30
9806.98658.327689819.32158.510769833.87558.134959843.96457.143949850.99356.16301
9856.28555.887489868.60656.985099893.24956.553589902.34556.308479905.588 56.3329
9930.44455.596629942.87255.409089952.88754.52617  9955.354.119399967.72850.62535
9969.72849.989189980.15645.64616 9986.5744.042569992.58443.50923    999943.68925
10005.0244.1640110029.8253.2358910037.2154.9361210042.2255.6841510054.6357.77841
10071.0259.0726410087.92  60.88110091.8461.2052710104.1261.6866810116.49 61.6786
#Mann= 3 , 0 , 0
9806.986    0.04       09806.986    0.04       010116.49    0.04       0
#XS Ineff= 2 , 0
       09896.069        10102.88       0
Bank Sta=9806.986,10116.49
Exp/Cntr=0.3,0.1

Type RM Length L Ch R = 1 , 5886.83,248.580300,248.580300,248.580300
XS GIS Cut Line= 5
929817.801321297811961.826067949929849.824661561811939.945806422
929967.621178815811864.472988918929969.321967791811863.420697675
930070.554787479811799.062812034
#Sta/Elev= 30
9820.31554.427199829.03354.313989841.14553.911529853.25652.122939859.09952.29021
9877.12253.311939888.999 53.5607 9905.3453.349979912.75253.519729942.41353.49623
9948.38153.625299960.25852.917619972.13449.884539979.48747.544919984.01146.25042
9995.88741.05711    999940.6791910007.7340.50639 10016.743.9539110019.5845.54714
10031.4350.4065310035.3351.5363110043.2853.5588410053.9755.1478910066.98 56.5658
10078.8356.8807110090.6857.5143710102.5357.6864310114.3858.0214410120.9657.94608
#Mann= 3 , 0 , 0
9820.315  0.0474       09820.315  0.0474       010120.96  0.0474       0
#XS Ineff= 2 , 0
       0 9908.32        10111.79       0
Bank Sta=9820.315,10120.96
Exp/Cntr=0.3,0.1

Type RM Length L Ch R = 1 ,5638.249,248.580300,248.580300,248.580300
XS GIS Cut Line= 6
929972.275866219812171.411192056930025.942271107812131.940648921
930109.658435566 812068.37532134930111.243239551812067.155322844
930203.636902675811997.641220741930204.243613113811997.208750027
#Sta/Elev= 30
9827.26850.859489843.06350.526729855.47648.516119871.84449.813979880.30350.28352
9888.72249.508449892.71649.283129917.81550.49559  9921.950.611959930.37150.49078
9938.436 49.98099942.92749.805869955.48350.033149968.03948.228649971.50947.47171
9980.59543.149239988.04539.446529993.15138.42176    999938.3873110004.5838.54002
 10005.738.6799310018.2243.5560410021.2244.2473510030.7346.9194210037.8549.19121
10043.24 50.235710055.7652.0631510080.79  53.18810105.8254.7891110117.3755.17219
#Mann= 3 , 0 , 0
9827.268  0.0636       09827.268  0.0636       010117.37  0.0636       0
#XS Ineff= 2 , 0
       09915.533           10114       0
Bank Sta=9827.268,10117.37
Exp/Cntr=0.3,0.1

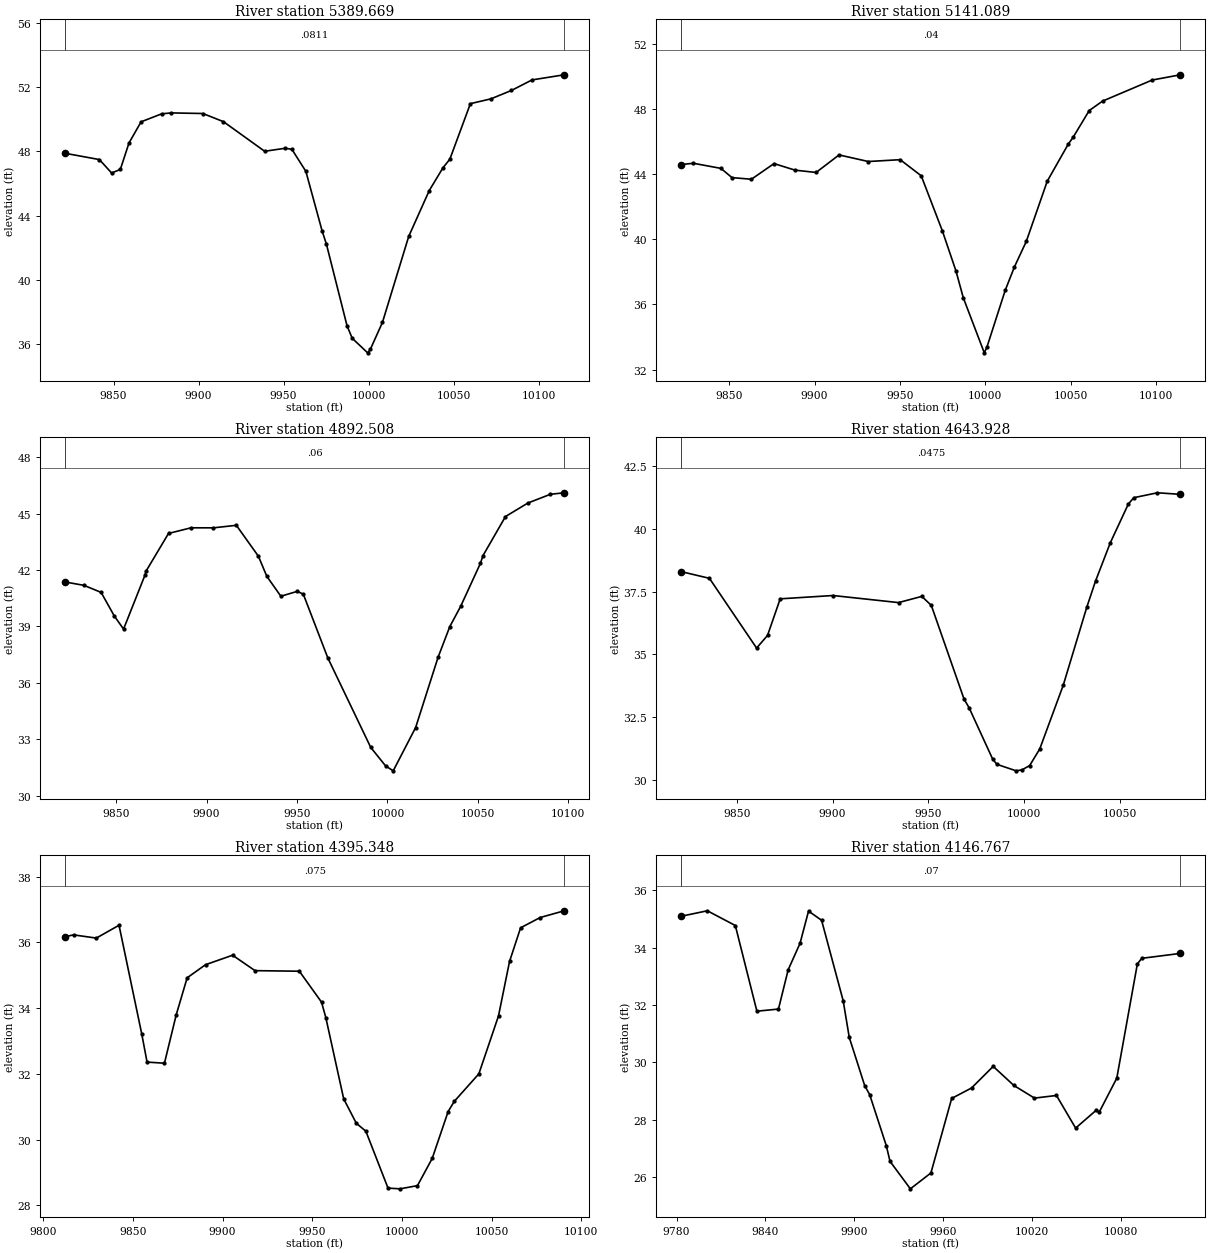
Type RM Length L Ch R = 1 ,5389.669,248.580400,248.580400,248.580400
XS GIS Cut Line= 5
930108.648913549812371.029710611930139.125751445812349.032059473
930254.651317835812270.117611629930256.313377506812269.005155945
930350.691368097812204.982154676
#Sta/Elev= 30
9821.50847.886629841.67347.495739848.89746.659179854.00646.881859859.09448.52746
9866.20849.843429878.31850.340739883.97150.398059902.53950.36014 9914.6549.85261
 9938.87 48.01159950.98148.200069954.88748.132369963.09146.763969972.615 43.0702
9975.20242.225299987.31237.153839990.34436.38164 9999.4235.47447   1000135.68956
10008.1337.3702310023.5842.7195810035.6645.5706310043.7646.9930210047.7547.51778
10059.8350.9727610071.9251.27231   1008451.7957110096.0852.4497110115.0452.76932
#Mann= 3 , 0 , 0
9821.508  0.0811       09821.508  0.0811       010115.04  0.0811       0
#XS Ineff= 2 , 0
       0 9918.84        10108.69       0
Bank Sta=9821.508,10115.04
Exp/Cntr=0.3,0.1

Type RM Length L Ch R = 1 ,5141.089,248.580300,248.580300,248.580300
XS GIS Cut Line= 5
930251.024117286812579.230044496930269.732539946 812565.42393674
930394.664428743812475.551835145930396.277580544812474.369574062
930488.481022402812408.431301112
#Sta/Elev= 27
 9821.8544.584199828.97444.660529845.10144.34697 9851.5943.781049862.95143.68097
9876.22744.641229888.54644.238579900.86444.096929914.32445.172989931.448 44.7686
9950.13944.880839962.45743.893419974.77640.534939982.82138.056139987.09536.41548
9999.41633.03398   1000133.3994110011.7236.8816910017.1138.3125410024.0239.86903
10036.3143.5631310048.6145.8337310051.4946.25954 10060.947.8939510068.6848.47176
10097.7849.7650410114.3550.08829
#Mann= 3 , 0 , 0
 9821.85    0.04       0 9821.85    0.04       010114.35    0.04       0
#XS Ineff= 2 , 0
       09917.733        10108.68       0
Bank Sta=9821.85,10114.35
Exp/Cntr=0.3,0.1

Type RM Length L Ch R = 1 ,4892.508,248.580400,248.580400,248.580400
XS GIS Cut Line= 5
930399.033084916812781.274032054930405.335716456812776.483237443
930541.607859137 812676.05074603930543.221010938812674.868484947
930621.174488759 812617.50096458
#Sta/Elev= 30
  9821.8 41.36379832.21741.185049841.72240.811619849.07239.548919854.14538.86284
9865.92841.715819866.56741.93823 9878.9943.940769891.41244.240399903.83444.23959
9916.49444.373579928.67942.732219933.34941.662639941.10240.606199950.20540.86597
9953.52440.71378 9967.0637.331179990.79132.57768    999931.5955310003.21 31.3334
10015.6233.6347210028.0437.3715310034.5238.9967110040.4640.0616210051.3942.34559
10052.8742.7674710065.2944.83986 10077.745.5581810090.1246.0210710097.7946.10102
#Mann= 3 , 0 , 0
  9821.8    0.06       0  9821.8    0.06       010097.79    0.06       0
#XS Ineff= 2 , 0
       09928.821        10095.43       0
Bank Sta=9821.8,10097.79
Exp/Cntr=0.3,0.1

Type RM Length L Ch R = 1 ,4643.928,248.580300,248.580300,248.580300
XS GIS Cut Line= 4
 930543.06478185812981.344273261930687.507780949812877.274296804
930689.144022672812876.124204189930754.797337065812829.197559004
#Sta/Elev= 25
9820.97138.302049835.68138.035759860.33235.251319866.03735.756049872.65737.21692
9900.25137.348799934.46437.066429946.60837.314069951.57136.955669968.67733.21358
9971.25932.877249983.58430.825559985.78430.611379995.90930.35072    999930.39183
10002.9330.56072 10008.231.2222910020.4933.7688110032.78  36.88210037.3337.92263
10045.0739.4562610054.5241.0066910057.3741.2539610069.6641.44979 10081.741.38748
#Mann= 3 , 0 , 0
9820.971  0.0475       09820.971  0.0475       0 10081.7  0.0475       0
#XS Ineff= 2 , 0
       09934.288        10079.95       0
Bank Sta=9820.971,10081.7
Exp/Cntr=0.3,0.1

Type RM Length L Ch R = 1 ,4395.348,248.580300,248.580300,248.580300
XS GIS Cut Line= 6
930681.240321215813193.064857772930760.271409147813131.635304252
930830.452987101813080.643058024930832.089228824813079.492965409
930896.176792142813033.346500792930904.601039416813026.935878257
#Sta/Elev= 30
9812.15236.171659816.91436.226599829.57936.128959842.24536.519269854.91133.21216
9857.883 32.35599867.57632.321769874.17733.801099880.24234.920699890.47235.31889
9905.57335.607979918.09435.138419942.81635.120879955.17734.180199957.56333.71181
9967.53831.237879974.57530.494529979.89930.25373 9992.2628.52188    999928.49957
10008.69 28.597210016.9129.42584 10025.830.8520610029.2331.1619810042.9231.99852
10053.8833.7615110060.0335.41821 10066.236.4418610077.1436.7553310090.5636.95992
#Mann= 3 , 0 , 0
9812.152   0.075       09812.152   0.075       010090.56   0.075       0
#XS Ineff= 2 , 0
       09910.953                       0
Bank Sta=9812.152,10090.56
Exp/Cntr=0.3,0.1

Type RM Length L Ch R = 1 ,4146.767,248.580400,248.580400,248.580400
XS GIS Cut Line= 6
930840.547798393813428.087988369930865.032214195813400.912965147
930951.219468986813309.641514892930988.888882032813271.309105161
930990.310168797813269.902000356931073.143948385813184.060876507
#Sta/Elev= 30
9783.14535.093429800.76135.283849819.67534.769469834.24131.780939848.80631.85603
9855.36333.225919863.37234.147729869.11735.272759877.93734.952099892.50232.14844
9896.625  30.8669907.06729.182239910.379 28.87459921.63327.091359924.13326.54591
9937.88725.585389951.76426.138989965.78428.738659979.18529.102589993.82529.85624
10007.8129.1899210021.7128.7501610036.5628.84211 10049.527.70327 10063.428.32784
10065.3628.25325 10077.329.4462210091.19 33.431710094.1633.6260310120.2933.79674
#Mann= 3 , 0 , 0
9783.145    0.07       09783.145    0.07       010120.29    0.07       0
#XS Ineff= 2 , 0
       09875.391        10119.85       0
Bank Sta=9783.145,10120.29
Exp/Cntr=0.3,0.1

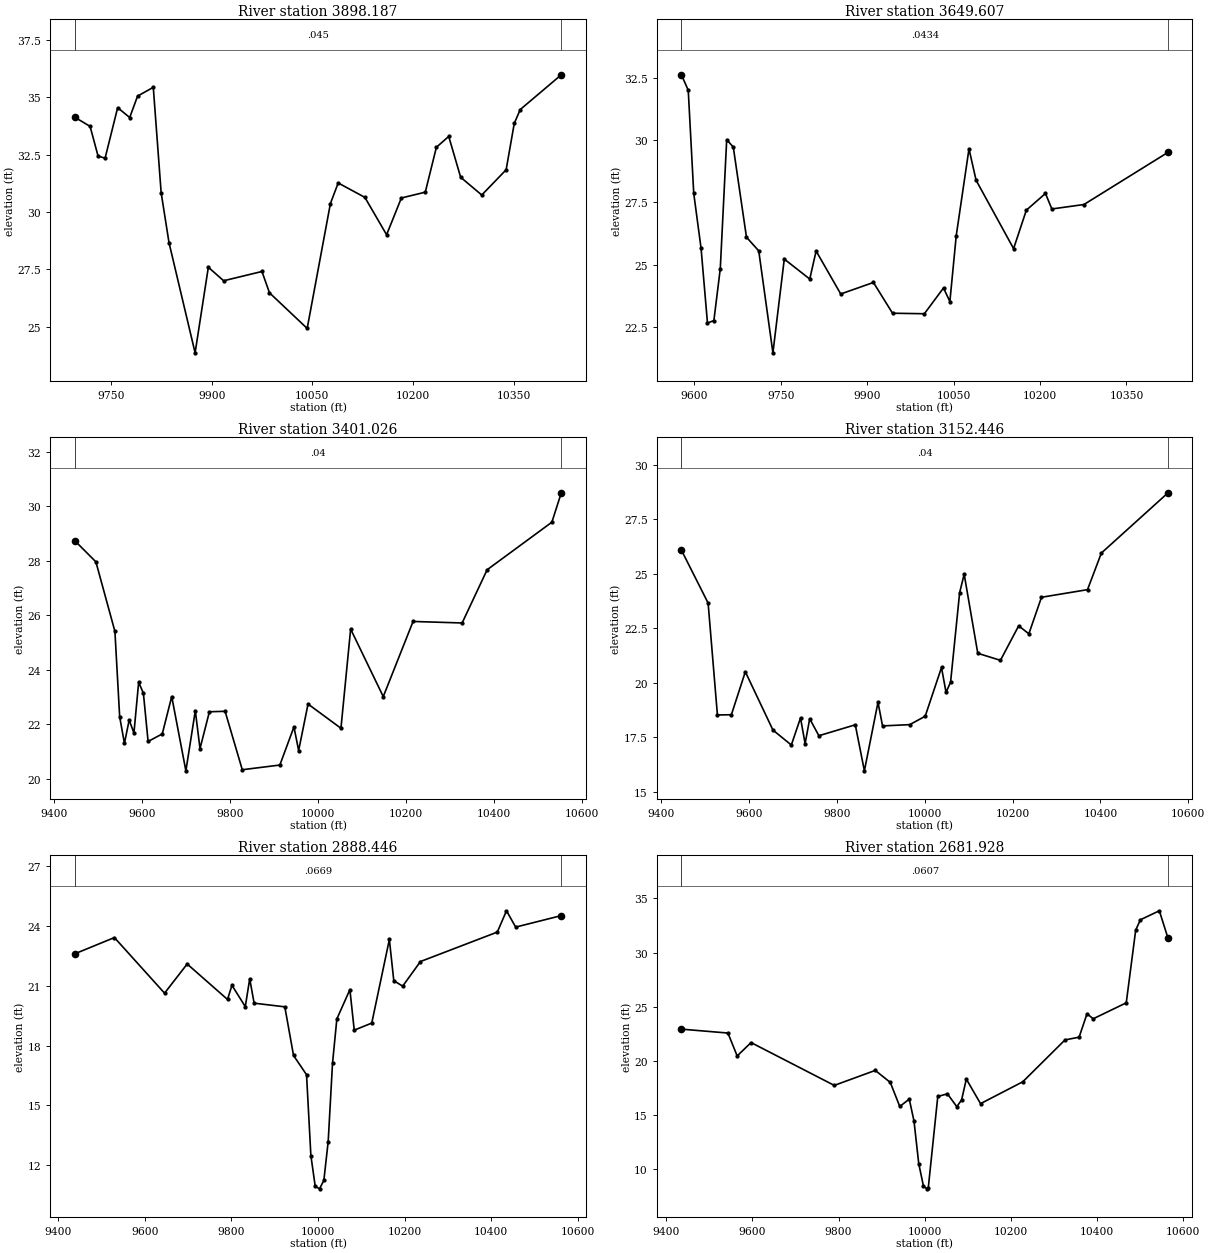
Type RM Length L Ch R = 1 ,3898.187,248.580300,248.580300,248.580300
XS GIS Cut Line= 6
931030.810290483813684.413845768  931130.5415034813522.696151397
931207.897131691813378.101905933931247.545946684813310.761678712
931312.622835314813209.153254099931409.411186932813067.087375702
#Sta/Elev= 30
9696.00334.133159718.968 33.73099730.79732.437239741.28532.344239760.00534.54811
 9777.9534.117949789.65735.05287 9813.0735.435819824.77630.835499836.48328.65723
9875.347  23.8519895.05327.585779917.83626.995889974.885 27.40049986.09526.47078
10042.2724.9155510076.8430.3635810088.4431.2624910128.1830.6342710160.5429.00265
10182.5230.6068210218.1430.86156 10234.732.8200610253.0633.2934710270.8231.51225
10302.2630.7364110338.5731.8384810350.6733.8623510359.6234.4677510420.7435.98297
#Mann= 3 , 0 , 0
9696.003   0.045       09696.003   0.045       010420.74   0.045       0
#XS Ineff= 2 , 0
       0 9767.64        10108.35       0
Bank Sta=9696.003,10420.74
Exp/Cntr=0.3,0.1

Type RM Length L Ch R = 1 ,3649.607,248.580400,248.580400,248.580400
XS GIS Cut Line= 6
931225.664214755813915.635194377931293.305222181813776.469983311
931406.518444938813535.309709424931503.527059434813329.737354876
931549.868165867813235.995227425931592.053675657813155.070850667
#Sta/Elev= 30
9577.85532.63709 9589.6832.013359599.21127.865979611.91725.660849623.03622.65173
9634.15422.750849645.27324.841689656.39230.028449667.838 29.72829690.71326.10284
9711.98525.555839736.576  21.4539756.30625.224149800.49424.421259811.54125.54821
9854.23523.820079910.96524.283759944.10723.046589999.349 23.025410032.5524.06245
 10043.623.5158310054.6626.1692110076.7729.6587110089.0728.3949310154.1625.64516
10176.2727.1906110209.4427.86443 10220.527.2395810276.2227.4188310422.1429.51935
#Mann= 3 , 0 , 0
9577.855  0.0434       09577.855  0.0434       010422.14  0.0434       0
#XS Ineff= 2 , 0
       09676.471        10088.58       0
Bank Sta=9577.855,10422.14
Exp/Cntr=0.3,0.1

Type RM Length L Ch R = 1 ,3401.026,248.580300,248.580300,248.580300
XS GIS Cut Line= 6
931439.681575289814139.550742639931489.014748904 814019.55958637
 931536.55470436813897.761175634931744.906755372813342.198117015
931797.686386547813213.412680458931843.770872629813110.415951916
#Sta/Elev= 30
 9447.0728.74665 9495.2427.967539538.488 25.41329549.30122.281429560.11321.30712
9570.92522.160519581.70221.685639592.43723.546979603.17123.147899613.90621.37487
 9646.1121.65238 9667.5823.024279699.78420.297099721.17622.503949731.85121.11265
9753.19922.465279788.87522.48183 9827.9220.337379913.31420.509899945.33721.90795
9956.01221.04197 9977.3622.7490310052.1421.8591910074.1825.4995310148.3123.02101
10216.0525.7793510327.5225.7235510384.3327.6760910531.4429.4221810552.9230.50175
#Mann= 3 , 0 , 0
 9447.07    0.04       0 9447.07    0.04       010552.92    0.04       0
#XS Ineff= 2 , 0
       09765.774         10083.9       0
Bank Sta=9447.07,10552.92
Exp/Cntr=0.3,0.1

Type RM Length L Ch R = 1 ,3152.446,264.000000,264.000000,264.000000
XS GIS Cut Line= 6
 931715.48174541814232.352890437931766.438173233814086.784131314
931810.914096452813942.280552336931952.419267096813411.284151803
931995.780145413813279.037000653932036.083376084813172.393429622
#Sta/Elev= 30
9445.91726.082479506.68223.658039527.87218.526949559.65718.538299591.44220.50802
9654.32817.83485 9696.18 17.14929717.10618.390629727.56917.212749738.03118.35328
9758.889 17.57569841.83818.076279862.562  15.9669893.54919.109449903.87818.02568
9965.852 18.0838   1000118.4685610038.1720.7036410048.4919.5648110058.8220.02779
10079.4724.1381110089.7924.9787510120.7721.35461 10172.421.0316910213.8822.61326
10237.0922.2480510265.85 23.923110370.6524.2719110402.2325.9502410554.0828.71291
#Mann= 3 , 0 , 0
9445.917    0.04       09445.917    0.04       010554.08    0.04       0
#XS Ineff= 2 , 0
       09920.845         10079.8       0
Bank Sta=9445.917,10554.08
Exp/Cntr=0.3,0.1

Type RM Length L Ch R = 1 ,2888.446,206.517700,206.517700,206.517700
XS GIS Cut Line= 6
931999.166631302814281.455016501932115.041299362813907.215006474
932132.220206907813804.674416216932141.428748238813650.905200555
932167.971196834813515.094071911932273.830772569 813196.44896319
#Sta/Elev= 30
9437.67522.58726 9529.4723.401549645.39520.619639697.64522.079579790.83920.30636
9801.13221.012829831.98719.945459842.17521.339449852.36320.119799923.314 19.9363
 9943.4417.503469973.51216.539429983.51512.498249993.51810.9633110003.5210.83049
10013.5211.2535710023.5313.1952710033.5317.1101410043.5619.33219 10073.720.79581
10083.7418.7687410124.2519.1232710164.9123.3050210175.1521.2445810195.6520.97002
10236.75 22.202210414.3823.6758710435.6124.7419210456.8423.9255610562.3124.50013
#Mann= 3 , 0 , 0
9437.675  0.0669       09437.675  0.0669       010562.31  0.0669       0
#XS Ineff= 2 , 0
       0                 10201.3       0
Bank Sta=9437.675,10562.31
Exp/Cntr=0.3,0.1

Type RM Length L Ch R = 1 ,2681.928,206.517800,206.517800,206.517800
XS GIS Cut Line= 6
932121.120266513  814315.5665457932257.677107785813963.867620403
932288.257901352813888.754174606 932381.88180069813687.269821218
932493.036017552813429.467546563932561.757246018 813276.52429955
#Sta/Elev= 30
9435.51822.907159543.39922.545169564.85420.426189597.03621.663839790.12817.69968
9885.25819.08808 9920.0517.978069942.06815.747529964.08716.429769975.09614.39401
9986.10510.452189997.1158.35741810005.418.12616410008.198.20746110030.2616.67417
10052.62 16.917710074.4215.7319810085.4616.35054 10096.518.2839510129.4416.01027
10227.4518.0351510325.4521.9110310358.1222.1616310376.5224.3355710390.7923.86376
 10467.525.3416710489.4232.0739810500.3833.0300810544.2433.8616710564.4931.30817
#Mann= 3 , 0 , 0
9435.518  0.0607       09435.518  0.0607       010564.49  0.0607       0
#XS Ineff= 2 , 0
       0                               0
Bank Sta=9435.518,10564.49
Exp/Cntr=0.3,0.1

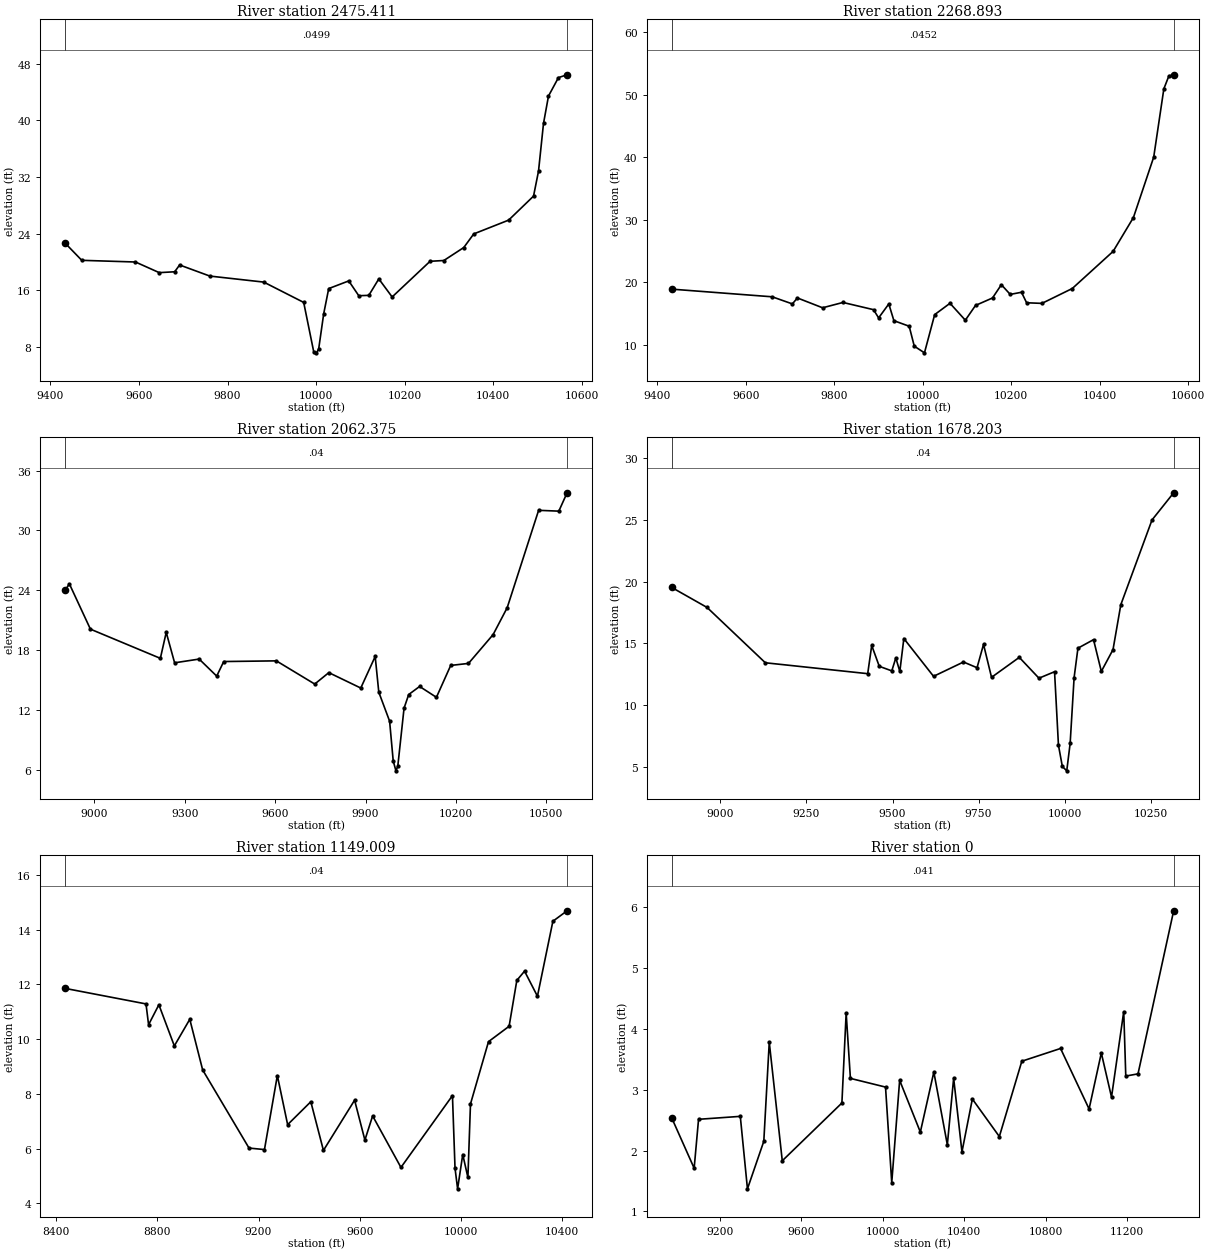
Type RM Length L Ch R = 1 ,2475.411,206.517700,206.517700,206.517700
XS GIS Cut Line= 6
932265.531363405814398.962138801932350.827291707814214.952652214
932428.136542542 814056.10296381932514.158225266813890.947831571
932629.977139543813672.424714518932776.794411585 813387.65933015
#Sta/Elev= 30
9433.30422.627429470.73820.205579591.98119.967849645.65718.464049680.55518.58551
9691.67619.547949759.91517.97711 9881.6817.125089971.88114.250949994.4317.296555
 10000.87.11521510005.737.66119810017.0512.6380610028.3716.2057210073.6417.29262
10096.2715.1982910118.9115.2483710141.5417.5762510171.6315.0212210257.2820.06883
10288.4220.1802410333.4322.0190810355.9323.9433710434.69 25.894110490.9429.29014
10502.1932.8284710513.4439.5742210524.6943.4519310547.1946.06187 10566.7   46.46
#Mann= 3 , 0 , 0
9433.304  0.0499       09433.304  0.0499       0 10566.7  0.0499       0
#XS Ineff= 2 , 0
       0                               0
Bank Sta=9433.304,10566.7
Exp/Cntr=0.3,0.1

Type RM Length L Ch R = 1 ,2268.893,206.517800,206.517800,206.517800
XS GIS Cut Line= 6
932424.131471636814485.990714194 932500.91108627 814337.66905597
932584.091378796814185.012604614932696.695453875813987.538756068
932861.215996995813702.288477479932977.061706905813495.649107302
#Sta/Elev= 30
9432.81418.86372 9659.8117.638369705.363 16.50139716.75117.454069773.69215.88049
9819.73916.733349888.80915.577659900.32114.261099923.34416.495919934.85613.81385
9969.39112.926069980.9039.73320910003.938.66673610027.0214.7848610061.6516.59934
10096.2813.8936310119.3716.2595110157.7317.4508610177.7419.5771210197.7618.02326
10223.2718.3651510234.8116.6825110269.4416.5862310338.0318.9668710430.3624.91456
10476.2230.3305510522.0840.0013110545.0150.9432210556.4753.0174610567.1953.18568
#Mann= 3 , 0 , 0
9432.814  0.0452       09432.814  0.0452       010567.19  0.0452       0
#XS Ineff= 2 , 0
       0                               0
Bank Sta=9432.814,10567.19
Exp/Cntr=0.3,0.1

Type RM Length L Ch R = 1 ,2062.375,384.172300,384.172300,384.172300
XS GIS Cut Line= 6
932302.931014016815036.883234061932736.957347632814307.909416581
 932806.90797255814195.701866822 932994.06379826813908.340142865
933084.004178128813759.566615991933168.743835943813613.180288139
#Sta/Elev= 30
8902.74524.014458916.58824.649258986.48220.111379218.72717.186729238.22319.78879
9266.05816.739719347.60117.114339405.84515.407569429.143 16.86739603.85716.93595
9731.34214.611919778.146 15.75639884.21514.212349932.09517.375529944.065 13.7981
9979.97510.895419991.9456.914886   100015.91912510007.216.39443210027.9312.19332
10043.4213.5636210079.63 14.371310135.4313.2833110182.8616.4777710241.9116.67932
10323.7119.5671710370.4522.2615510474.7732.0138310541.8831.9320210569.3133.77145
#Mann= 3 , 0 , 0
8902.745    0.04       08902.745    0.04       010569.31    0.04       0
#XS Ineff= 2 , 0
       0                               0
Bank Sta=8902.745,10569.31
Exp/Cntr=0.3,0.1

Type RM Length L Ch R = 1 ,1678.203,529.193600,529.193600,529.193600
XS GIS Cut Line= 6
932615.431014016 815292.95962295932982.851418309 814679.60749685
933036.941382774814583.935242781933104.836176598814469.424413077
933152.323977985814384.279955529933340.287869172 814029.41040756
#Sta/Elev= 30
8859.18719.531628961.72117.912349130.78113.435269427.99912.552579439.65614.83641
9461.59213.147989497.94112.778799509.59813.828159521.25412.730489532.91115.39855
9619.17112.336939706.10313.497719745.40613.034079764.26114.921899787.49112.25549
9868.06513.872649925.19212.186219970.456   12.719981.7726.7626059993.0885.037421
10005.874.68482110015.72 6.9039110027.2312.2356210038.3514.6169210083.6215.30685
10106.2512.73541 10140.214.5008510162.8318.1366410253.3624.9968110316.2727.19949
#Mann= 3 , 0 , 0
8859.187    0.04       08859.187    0.04       010316.27    0.04       0
#XS Ineff= 2 , 0
       0                10316.05       0
Bank Sta=8859.187,10316.27
Exp/Cntr=0.3,0.1

Type RM Length L Ch R = 1 ,1149.009,1149.009200,1149.009200,1149.009200
XS GIS Cut Line= 2
933389.909343179816018.784860824933769.079372773814069.850908712
#Sta/Elev= 30
8435.12811.854988754.79611.288538764.98410.529298805.73411.257968866.8599.755097
8927.98410.726888978.921 8.877369162.2966.0239699223.4215.9687749274.3598.672262
9315.1086.8788659406.7967.7162149456.6955.9377729579.9837.7723639620.733 6.31578
9651.2967.1986929763.3585.3173089967.1087.9394999977.2965.2874559987.4834.534741
10007.865.78840410028.234.95112810038.42 7.6340910109.739.91034310191.2310.47188
 10221.812.1484210252.3612.48493 10303.311.5696510364.42 14.3072 10420.614.69018
#Mann= 3 , 0 , 0
8435.128    0.04       08435.128    0.04       0 10420.6    0.04       0
#XS Ineff= 2 , 0
       08922.611        10271.01       0
Bank Sta=8435.128,10420.6
Exp/Cntr=0.3,0.1

Type RM Length L Ch R = 1 ,       0,0.000000,0.000000,0.000000
XS GIS Cut Line= 6
934166.178877264816176.840499018934446.337290328815507.611191594
934517.583031439815247.022670031934521.573082139815171.460699723
934356.884005469814651.199473377934339.856761879813810.053640044
#Sta/Elev= 30
8965.4022.5347789075.2041.7091659096.7682.5134429301.6232.5619349336.7251.369878
 9416.972.1517789443.7193.7824999507.588 1.831279800.1952.7815889821.0784.261981
9841.9623.18631910014.263.04347510044.771.47157310083.553.15485510185.122.303351
10251.333.29060610317.542.09530410348.54 3.1888810389.311.97720210440.282.847145
10572.792.22976410683.073.46877510873.113.67847311013.142.68360411073.153.603958
11123.162.87868711183.174.28428511193.183.22449711253.193.26081511428.175.942958
#Mann= 3 , 0 , 0
8965.402   0.041       08965.402   0.041       011428.17   0.041       0
#XS Ineff= 2 , 0
       0 9290.21        10853.29       0
Bank Sta=8965.402,11428.17
Exp/Cntr=0.3,0.1